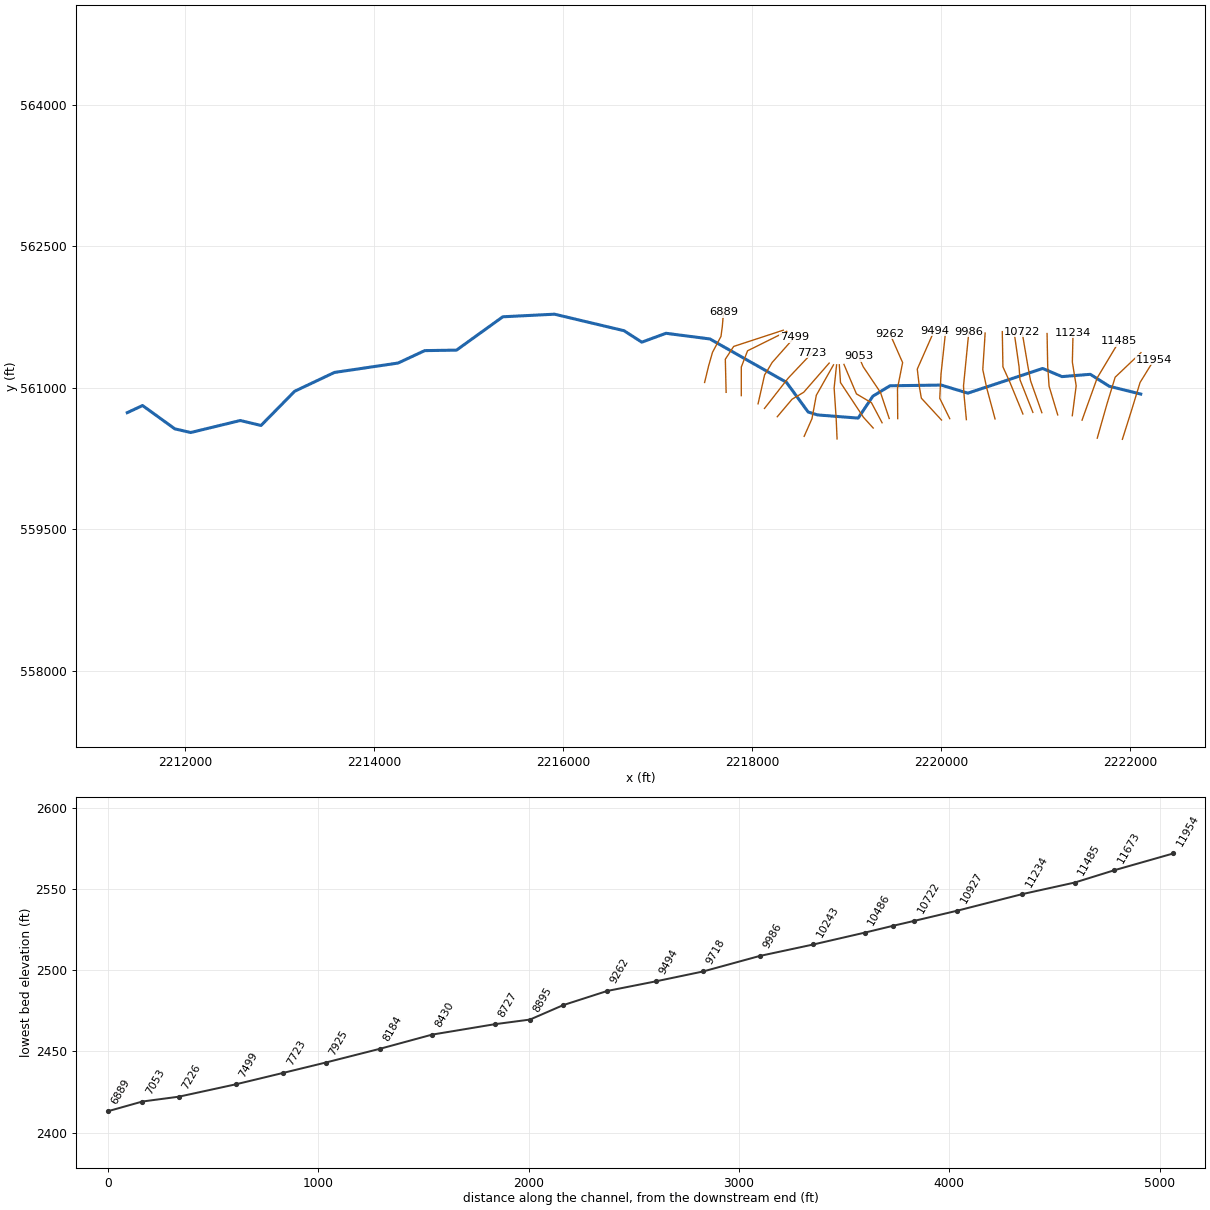
--- VALLEYFK.prj (project) ---

Proj Title=VALLEYFK
Current Plan=p01
Default Exp/Contr=0,0
English Units
Geom File=g01
Flow File=f01
Plan File=p01
Background Map Layer=Inundation Boundary (P100yr Value_0)
BEGIN DESCRIPTION:
----------MODEL BY WOOD PLC 2022----------
AFH study
Randolph County, WV
HEC-RAS Version: RAS 6.2
Vertical Datum: NAVD88
Projection: NAD 1983 StatePlane West Virginia S FIPS 4702 (US Feet)
Terrain: 1-meter LIDAR (FEMA Region III 3DEP collected 2016-2018)
Land Use: 2019 NLCD
Hydrologic Method:
WV SIR2010-5033 regression equations
Additional Model Notes:
VALLEYFK Lower Reach
Split VALLEYFK at the confluence with MUDLKRN
END DESCRIPTION:
DSS Export Rating Curves= 0
DSS Export Rating Curve Sorted= 0
DSS Export Volume Flow Curves= 0
DXF OffsetX= 0
DXF OffsetY= 0
DXF ScaleX= 0
DXF ScaleY= 0

--- VALLEYFK.p01 (plan) ---

Plan Title=Floodplain
Program Version=6.20
Short Identifier=Floodplain
Geom File=g01
Flow File=f01
Subcritical Flow
K Sum by GR= 0
Std Step Tol= 0.01
Critical Tol= 0.01
Num of Std Step Trials= 20
Max Error Tol= 0.3
Flow Tol Ratio= 0.001
Split Flow NTrial= 30
Split Flow Tol= 0.02
Split Flow Ratio= 0.02
Log Output Level= 0
Friction Slope Method= 1
Unsteady Friction Slope Method= 2
Unsteady Bridges Friction Slope Method= 1
Parabolic Critical Depth
Global Vel Dist= 0 , 0 , 0
Global Log Level= 0
CheckData=True
Encroach Param=-1 ,0,0, 0
Mapping Interval=1HOUR
Computation Time Step Use Courant=        0
Computation Time Step Use Time Series=    0
Computation Time Step Count To Double=0
Computation Time Step Max Doubling=0
Computation Time Step Max Halving=0
Computation Time Step Residence Courant=0
Run HTab= 0
Run UNet= 0
Run Sediment= 0
Run PostProcess= 0
Run WQNet= 0
Run RASMapper=-1
UNET Theta= 0
UNET Theta Warmup= 0
UNET ZTol= 0
UNET ZSATol= 0
UNET MxIter= 0
UNET Max Iter WO Improvement= 0
UNET MaxInSteps= 0
UNET DtIC= 0
UNET DtMin= 0
UNET MaxCRTS= 0
UNET WFStab= 0
UNET SFStab= 0
UNET WFX= 1
UNET SFX= 1
UNET Gravity=32.174
UNET 1D Methodology=Finite Difference
UNET DSS MLevel= 1
UNET Pardiso=0
UNET DZMax Abort= 0
UNET Use Existing IB Tables= 0
UNET Froude Reduction=False
UNET Froude Limit= 0
UNET Froude Power= 0
UNET D1 Cores= 0
UNET WindReference=Eulerian
UNET WindDragFormulation=Hsu (1988)
UNET D2 Coriolis=0
UNET D2 Cores= 0
UNET D2 Theta= 1
UNET D2 Theta Warmup= 1
UNET D2 Z Tol= 0.01
UNET D2 Volume Tol= 0.01
UNET D2 Max Iterations= 20
UNET D2 Equation= 0
UNET D2 RampUpFraction=0.1
UNET D2 TimeSlices= 1
UNET D2 Turbulence Formulation=Non-Conservative (original)
UNET D2 Eddy Viscosity=0.3
UNET D2 Transverse Eddy Viscosity=0.1
UNET D2 Smagorinsky Mixing=0
UNET D2 BCVolumeCheck=0
UNET D2 Cores=0
UNET D2 SolverType=PARDISO (Direct)
UNET D2 Minimum Iterations= 2147483647
UNET D2 Maximum Iterations= 2147483647
UNET D2 Restart Number= 10
UNET D2 Relaxation Coeff=1.3
UNET D2 SOR Precondition Iterations= 10
UNET D2 ILUT Maximum Fill= 8
UNET D2 ILUT Tolerance=1E-08
UNET D1D2 MaxIter= 0
UNET D1D2 ZTol=0.01
UNET D1D2 QTol=0.1
UNET D1D2 MinQTol=1
Write IC File= 0
Write IC File at Fixed DateTime=0
Write IC File at Sim End=0
Echo Input=False
Echo Parameters=False
Echo Output=False
Write Detailed= 0
HDF Write Warmup=0
HDF Write Time Slices=0
HDF Flush=0
HDF Compression= 1
HDF Chunk Size= 1
HDF Spatial Parts= 1
HDF Use Max Rows=0
HDF Fixed Rows= 1
Calibration Method= 0
Calibration Iterations= 20
Calibration Max Change=0.05
Calibration Tolerance=0.2
Calibration Maximum=1.5
Calibration Minimum=0.5
Calibration Optimization Method= 1
WQ AD Non Conservative
WQ ULTIMATE=-1
WQ Max Comp Step=1HOUR
WQ Output Interval=15MIN
WQ Output Selected Increments= 0
WQ Output face flow=0
WQ Output face velocity=0
WQ Output face area=0
WQ Output face dispersion=0
WQ Output cell volume=0
WQ Output cell surface area=0
WQ Output cell continuity=0
WQ Output cumulative cell continuity=0
WQ Output face conc=0
WQ Output face dconc_dx=0
WQ Output face courant=0
WQ Output face peclet=0
WQ Output face adv mass=0
WQ Output face disp mass=0
WQ Output cell mass=0
WQ Output cell source sink temp=0
WQ Output nsm pathways=0
WQ Output nsm derived pathways=0
WQ Create Restart=0
WQ Fixed Restart=0
WQ System Summary=0
WQ Write To DSS=0
Sorting and Armoring Iterations= 10
XS Update Threshold= 0.02
Bed Roughness Predictor= 0
Hydraulics Update Threshold= 0.02
Energy Slope Method= 1
Volume Change Method= 1
Sediment Retention Method= 0
Sediment TS Multiplier= 1
Warm Up Method= 0
XS Weighting Method= 0
Number of US Weighted Cross Sections= 1
Number of DS Weighted Cross Sections= 1
Upstream XS Weight=0
Main XS Weight=1
Downstream XS Weight=0
Number of DS XS's Weighted with US Boundary= 1
Upstream Boundary Weight= 1
Weight of XSs Associated with US Boundary= 0
Number of US XS's Weighted with DS Boundary= 1
Downstream Boundary Weight= 0.5
Weight of XSs Associated with DS Boundary= 0.5
Percentile Method= 0
Sediment Output Level= 3
Mass or Volume Output= 0
Output Increment Type= 1
Profile and TS Output Increment= 1
Transport Output Increment 1
XS Output Flag= 0
XS Output Increment= 10
Read HDF5 Sediment Hotstart= 0
Sediment Hotstart Type= 0
Write Gradation File= 0
Read Gradation Hotstart= 0
Write HDF5 File= 1
Write Binary Output= 1
Write DSS Sediment File= 0
DSS Sediment Output Type= 1
SV Curve= 0
Specific Gage Flag= 0
Subcell Erosion Methods= 0
Subcell Deposition Methods= 0
Advection Scheme= 1
Matrix Solver= 0
Implicit Weighting Factor= 1
Maximum Outer Loop Convergence Iterations= 5
Convergence Maximum Absolute= 0.001
Convergence RMSE= 0.0001
Grain Fractions Max Abs Error= 0.001
Max Subgrid Regions= 1
Max Subgrid Length Scale= 3.402823E+38
Initial Layer Thickness= 3.402823E+38
Min Layer Thickness= 3.402823E+38
Max Layer Thickness= 3.402823E+38
Number of Layers= 5

--- VALLEYFK.f01 (steady flow) ---

Flow Title=Flow
Program Version=6.20
Number of Profiles= 1
Profile Names=P100yr
River Rch & RM=VALLEYFK,Main            ,11954
     971
River Rch & RM=VALLEYFK,Main            ,9986
    1200
River Rch & RM=VALLEYFK,Main            ,7226
    1430
River Rch & RM=VALLEYFK,Main            ,6247
    1600
Boundary for River Rch & Prof#=VALLEYFK,Main            , 1
Up Type= 0
Dn Type= 3
Dn Slope=0.01731
DSS Import GetInterval= 0
DSS Import GetPeak= 0
DSS Import FillOption= 0

--- VALLEYFK.g01 (geometry) ---

Geom Title=Geometry
Program Version=6.20

River Reach=VALLEYFK        ,Main
Reach XY= 30
     2222115.939      560933.764     2221782.038      561016.536
     2221581.715      561143.179     2221281.593      561118.814
      2221077.08      561204.925     2220285.066      560943.467
 2220003.7629719561029.069268394      2219461.31      561021.794
     2219279.886      560911.551     2219124.276      560679.356
     2218691.916      560713.105     2218594.506      560744.135
     2218364.434      561058.758     2217554.805      561517.715
     2217089.782      561577.7842216833.83033608561483.683282813
2216645.25146564561605.186130226     2215909.661      561780.041
     2215362.539      561752.547     2214872.296      561399.379
     2214535.662      561394.073     2214253.966      561262.657
     2213579.799      561162.8532213159.06302816 560963.68331243
      2212802.89      560601.221     2212582.838      560653.739
     2212058.251      560526.536     2211890.116      560565.437
     2211548.786      560812.447     2211386.769      560736.893

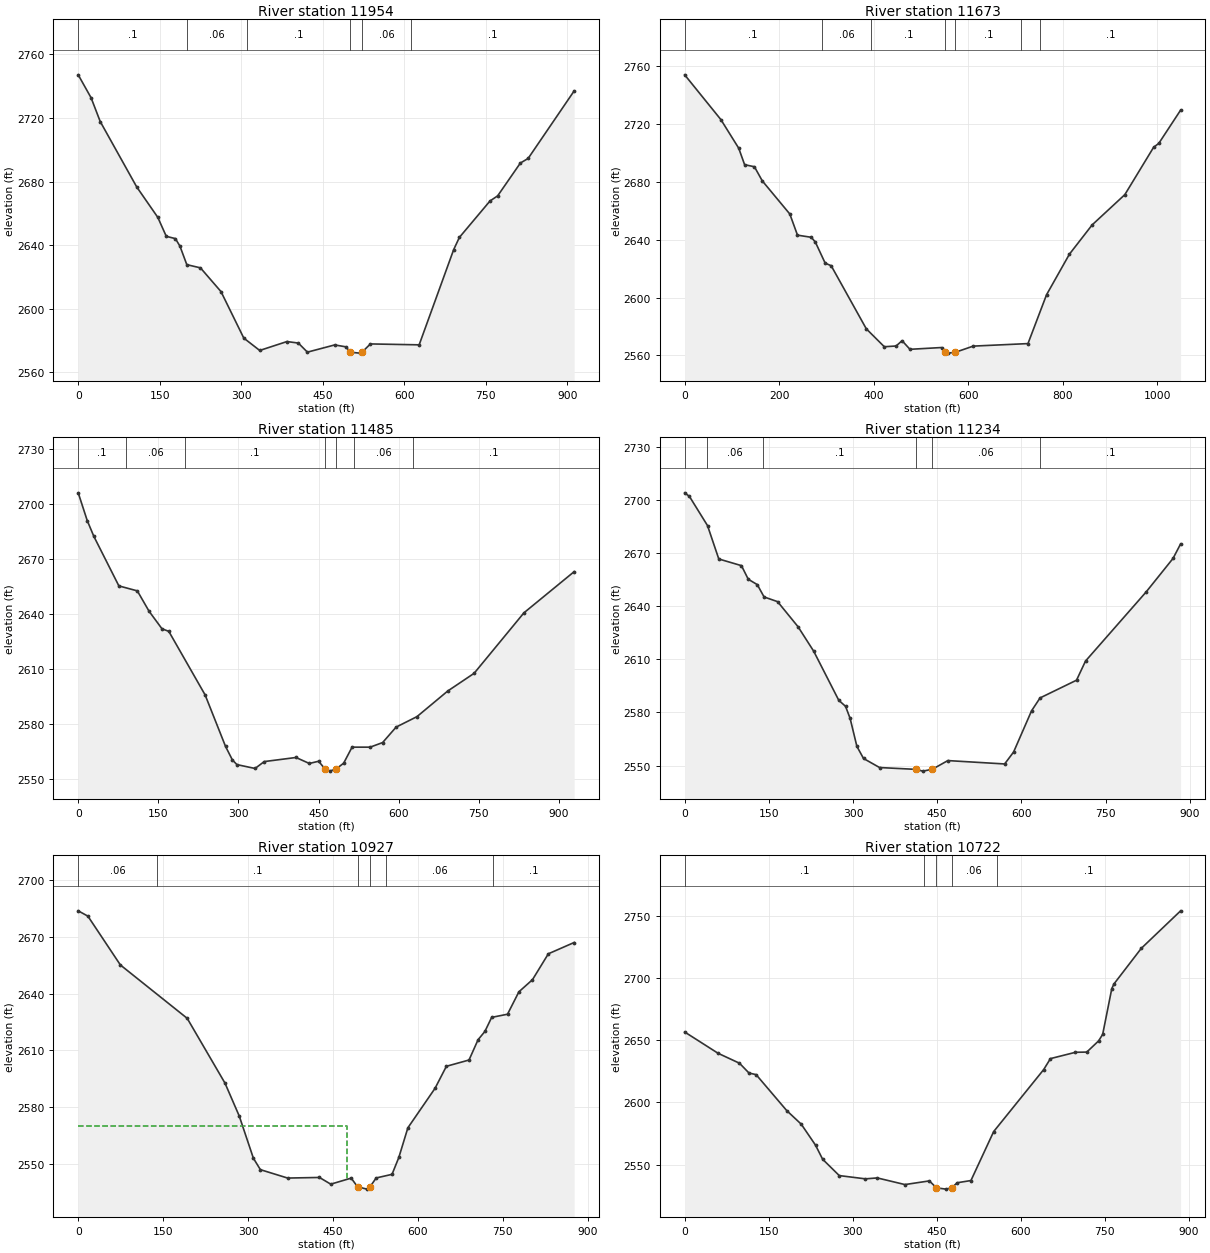
Type RM Length L Ch R = 1 ,11954   ,280.9,281.5,281.1
XS GIS Cut Line= 4
2221921.10088019560454.6083333922222021.52286492560772.162083642
2222108.41507758 561056.807920222222256.68862714561296.978951876
#Sta/Elev= 30
       0 2747.18    23.7 2732.73    40.5 2717.78   107.6 2676.64   146.5 2657.45
   162.1 2645.51   178.9 2644.06   187.3 2639.29   199.9 2627.67     225 2625.66
   262.8 2610.72   304.8 2581.43   334.1 2573.65   384.3 2579.26   405.2  2578.3
   421.9 2572.59   472.1 2577.13     493 2575.92  500.62 2572.55   518.1 2571.97
   522.3 2572.53   537.9 2577.76   627.6 2577.19   691.1  2637.1   701.6 2644.81
     758 2667.76   772.1 2670.99   813.9 2691.64   828.2 2694.54   912.9 2737.05
#Mann= 6 ,-1,0
       0      .1       0     200     .06       0     310      .1       0
  500.62    .045       0   522.3     .06       0  613.05      .1       0
Bank Sta=500.62,522.3
XS Rating Curve= 0 ,0
Exp/Cntr(USF)=0,0
Exp/Cntr=0.3,0.1

Type RM Length L Ch R = 1 ,11673   ,187.2,187.6,185.2
XS GIS Cut Line= 4
2221655.23080086 560467.187677332221757.74990596560827.732395241
2221844.64211862561112.3782318192222117.57782373561372.355400337
#Sta/Elev= 30
       0 2753.97    76.6 2723.02   114.4 2703.22   126.8 2691.86   147.6 2690.42
   164.2 2680.67   222.5 2657.74   238.7 2643.14   267.9 2641.66   276.5 2638.36
   297.3 2623.78     310 2622.01   384.3  2578.4   422.4 2566.01   447.4 2566.52
     460 2570.18   476.7 2564.23   543.6 2565.46  551.542562.127   556.2 2561.59
  572.692562.171   610.6 2566.44   726.4 2568.18   765.7 2601.94   814.1 2629.99
   862.2 2650.23   931.4 2671.16   992.2 2703.85  1003.3 2706.62  1049.4 2729.57
#Mann= 7 ,-1,0
       0      .1       0     290     .06       0  394.84      .1       0
  551.54    .045       0  572.69      .1       0  712.45     .06       0
  752.45      .1       0
Bank Sta=551.54,572.69
XS Rating Curve= 0 ,0
Exp/Cntr(USF)=0,0
Exp/Cntr=0.3,0.1

Type RM Length L Ch R = 1 ,11485   ,244.2,251.2,258.2
XS GIS Cut Line= 3
       2221494.2        560657.6     2221655.505      561106.715
     2221887.444      561493.795
#Sta/Elev= 30
       0 2705.83    16.9 2690.68    29.3 2682.06    76.1 2655.07   110.7 2652.34
   132.6 2641.26   156.8 2631.68   169.6 2630.27   237.6  2595.6   275.8 2567.53
   288.6 2560.16   297.1 2557.59   331.1 2555.48   348.3 2559.24   407.7 2561.47
   432.7 2558.21   450.1 2559.42   461.72555.337   471.3 2554.03  483.532555.336
     497 2558.38   512.7 2567.11   546.6 2567.11   569.9 2569.61   595.2 2578.05
   634.2 2583.75   691.8 2597.72   741.2 2607.38   834.5 2640.39   928.5 2662.83
#Mann= 7 ,-1,0
       0      .1       0      90     .06       0     200      .1       0
   461.7    .045       0  483.53      .1       0   517.2     .06       0
   627.2      .1       0
Bank Sta=461.7,483.53
XS Rating Curve= 0 ,0
Exp/Cntr=0.3,0.1

Type RM Length L Ch R = 1 ,11234   ,308.3,306.4,302.2
XS GIS Cut Line= 4
2221390.96603592560704.8533009242221432.08556689561022.144721866
2221391.65387488561271.9918442792221398.95756313 561582.62338454
#Sta/Elev= 30
       0 2704.11     8.4 2702.11    40.7 2685.59    60.8 2666.73   101.2 2662.96
   113.3 2655.28   129.4 2652.23   141.5 2645.27   165.6 2642.61     202 2628.45
   229.9 2614.63   274.6 2586.88   286.7 2583.46   294.8 2576.67   306.9 2560.83
   318.7    2554   347.3 2548.88  411.452547.855   424.3 2546.85  441.072547.855
     469 2552.81   570.2  2550.9   586.2 2557.67   618.2 2580.95   633.3 2588.21
   698.3 2598.23   714.3 2609.04   822.3 2648.08   870.3 2667.05   883.8 2675.26
#Mann= 6 ,-1,0
       0      .1       0      40     .06       0     140      .1       0
  411.45    .045       0  441.07     .06       0  633.04      .1       0
Bank Sta=411.45,441.07
XS Rating Curve= 0 ,0
Exp/Cntr(USF)=0,0
Exp/Cntr=0.3,0.1

Type RM Length L Ch R = 1 ,10927   ,204,205.3,206.4
XS GIS Cut Line= 4
2221236.61556796560712.7925994292221145.20488929561017.468638686
2221130.51227431561232.0099645142221123.92490698561574.799017582
#Sta/Elev= 30
       0 2683.72    17.1 2680.91    74.5 2655.12   192.5 2626.94   259.3 2592.69
   284.4 2575.36   309.4 2553.06   321.8    2547   369.9 2542.57   426.1 2542.88
   446.1 2539.34   482.2 2542.54  493.532537.892   510.2 2536.72  515.272537.887
   526.3 2542.62   554.3 2544.53   566.3 2553.44   582.3 2569.11   630.3 2589.98
   650.3  2601.6   690.3 2604.92   706.3 2615.65   718.3 2619.99   730.3 2627.44
   758.3 2629.11   778.4 2640.94   802.4 2647.35   830.4 2661.02     876 2666.99
#Mann= 6 ,-1,0
       0     .06       0     140      .1       0  493.53    .045       0
  515.27      .1       0  543.14     .06       0  733.14      .1       0
#XS Ineff= 2 , 0
             475    2570
Permanent Ineff=
       F       F
Bank Sta=493.53,515.27
XS Rating Curve= 0 ,0
Exp/Cntr=0.3,0.1

Type RM Length L Ch R = 1 ,10722   ,101.2,99.6,98.4
XS GIS Cut Line= 4
2221068.68552308560736.863845278 2220949.4319182561074.181184813
2220922.17395137561221.8285051492220858.89041402 561594.32405713
#Sta/Elev= 30
       0 2656.61    59.7  2639.5    97.9 2631.53   114.9 2623.65   127.6 2622.37
   182.4 2593.43   208.2 2582.58   233.7 2565.74   246.4 2554.42   276.1  2541.3
   322.8 2538.67     344 2539.42   393.4 2534.08     437 2537.03  449.752531.446
   466.6 2530.42  476.572531.447   486.9 2535.55   511.3 2537.32   551.9 2576.64
   641.2 2626.41   653.3 2635.23     698 2640.31   718.2 2640.48   739.3 2649.45
   746.6 2654.73   762.9 2691.52   766.9 2695.29   815.6  2723.8   885.8 2753.91
#Mann= 5 ,-1,0
       0      .1       0  427.78     .06       0  449.75    .045       0
  476.57     .06       0  557.92      .1       0
Bank Sta=449.75,476.57
XS Rating Curve= 0 ,0
Exp/Cntr(USF)=0,0
Exp/Cntr=0.3,0.1

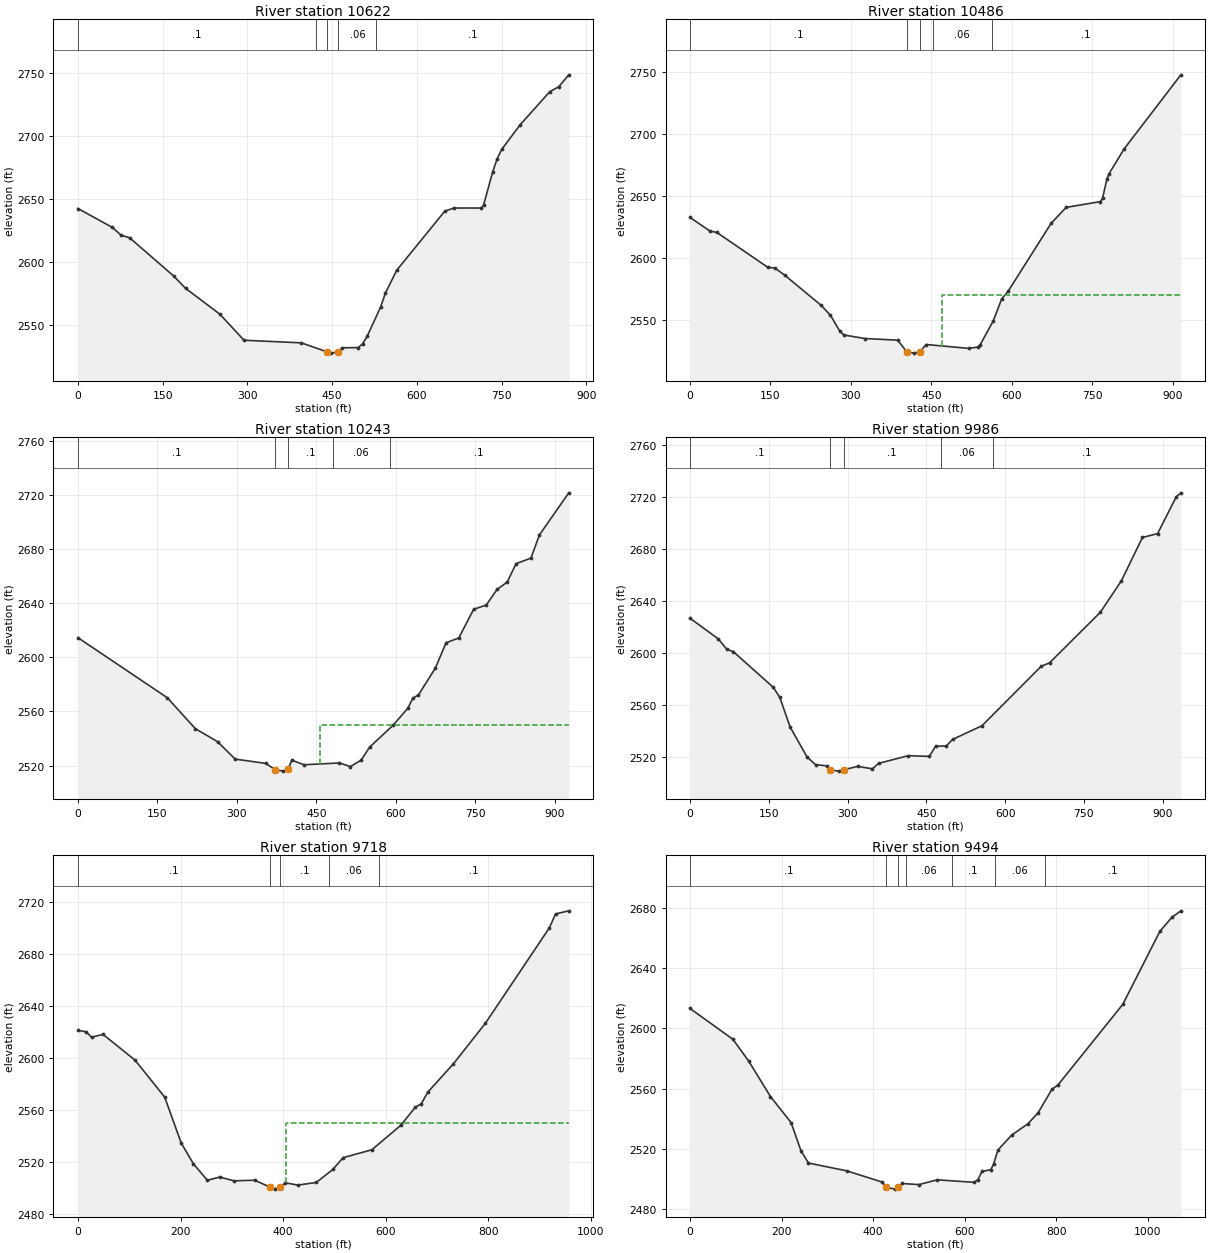
Type RM Length L Ch R = 1 ,10622   ,131.9,136,139.5
XS GIS Cut Line= 5
2220973.81182894 560739.769297182220843.82199235 561068.46971199
2220837.17598267561085.744500764 2220827.6045747 561221.35927474
2220776.70461919561578.603965914
#Sta/Elev= 30
       0 2642.52    60.9 2627.49    76.3 2621.33    91.5 2619.23   169.3 2588.84
   190.4 2579.03     251 2558.48     294 2537.68   395.5 2535.61  440.262528.542
   447.6 2527.43  461.18 2528.54   467.7 2531.68     496 2531.83   503.7 2534.77
   511.8 2540.77   535.6 2563.95   544.1 2575.08   564.3 2593.44   649.2 2640.36
   665.3 2642.92   713.8 2642.93   717.9 2645.17     734 2671.52   742.1 2682.19
   750.2 2689.65   782.5 2709.05     835 2735.45   851.2  2739.5   868.8 2748.94
#Mann= 5 ,-1,0
       0      .1       0  421.98     .06       0  440.26    .045       0
  461.18     .06       0  527.93      .1       0
Bank Sta=440.26,461.18
XS Rating Curve= 0 ,0
Exp/Cntr(USF)=0,0
Exp/Cntr=0.3,0.1

Type RM Length L Ch R = 1 ,10486   ,246.2,243.9,240.5
XS GIS Cut Line= 5
2220868.38346714560722.9209229032220718.89139558561086.759348327
2220710.00903317561104.1660221132220656.61876353561222.068788208
2220649.99930506561595.203890854
#Sta/Elev= 30
       0 2632.48      37 2621.55      50  2620.4   145.1 2592.27   158.1 2591.75
   176.6 2585.98   244.6 2561.64   261.9 2553.66   279.2 2540.99   286.9 2537.78
   326.8 2534.91   387.3 2533.63  404.292524.204   418.1 2523.17   428.62524.205
   440.4 2530.12   519.4 2527.02     537 2528.05   541.3 2530.01   565.5 2549.11
   581.4 2566.97     593 2572.84   673.5 2627.74   701.5  2640.6   765.5 2645.26
   769.5 2648.21   777.5 2663.17   781.5 2667.73   809.5 2687.62   915.5  2747.4
#Mann= 5 ,-1,0
       0      .1       0  404.29    .045       0   428.6      .1       0
  452.89     .06       0  562.32      .1       0
#XS Ineff= 2 , 0
                          469.45            2570
Permanent Ineff=
       F       F
Bank Sta=404.29,428.6
XS Rating Curve= 0 ,0
Exp/Cntr=0.3,0.1

Type RM Length L Ch R = 1 ,10243   ,257.1,256.1,253
XS GIS Cut Line= 4
2220573.24638616 560670.573787422220484.65799396560999.940886632
2220443.49923295561192.9467335422220468.46783568561580.422336995
#Sta/Elev= 30
       0 2614.45   168.4 2570.18   221.7 2547.26   263.7 2537.61   296.8 2524.78
   354.6 2521.61  371.782517.091   387.3 2515.89  396.582517.093   403.7 2523.98
   426.8  2520.6   493.7 2521.92   514.4 2519.25   534.6 2523.99   550.7  2533.6
   594.8 2549.72   622.8 2562.31   632.2 2569.72   642.9 2572.17   674.9 2592.06
     695 2610.71     719 2614.24   747.1 2635.43   771.1 2638.63   791.2 2650.09
   810.4  2655.5   827.2 2669.15   855.3 2673.28   871.3 2690.37   926.7 2721.47
#Mann= 5 ,-1,0
       0      .1       0  371.78    .045       0  396.58      .1       0
  481.07     .06       0  588.42      .1       0
#XS Ineff= 2 , 0
                          456.86            2550
Permanent Ineff=
       F       F
Bank Sta=371.78,396.58
XS Rating Curve= 0 ,0
Exp/Cntr(USF)=0,0
Exp/Cntr=0.3,0.1

Type RM Length L Ch R = 1 ,9986    ,270.8,268.3,265
XS GIS Cut Line= 4
2220269.63006304560663.2906299542220247.08765586560900.588941244
2220239.21488944561019.2972481472220295.82229521561594.022161877
#Sta/Elev= 30
       0 2626.74    53.8 2610.77    70.2  2602.7    82.3    2601   158.6  2573.4
   170.7 2565.85   190.7 2542.74   222.9 2519.68     239 2513.76   260.5 2512.87
  266.442509.782     283 2508.78  292.392509.779   319.1 2512.47   347.2 2510.57
   359.2 2514.77   415.5 2520.69   455.7 2520.14   467.7 2528.02     488 2528.16
   499.9  2533.2   556.2 2543.86   668.7  2589.6   684.8 2592.37   781.3 2631.28
   821.5  2655.6   861.6 2689.05   890.5 2692.01     926 2720.46   934.8 2723.48
#Mann= 5 ,-1,0
       0      .1       0  266.44    .045       0  292.39      .1       0
  477.34     .06       0  577.34      .1       0
Bank Sta=266.44,292.39
XS Rating Curve= 0 ,0
Exp/Cntr=0.3,0.1

Type RM Length L Ch R = 1 ,9718    ,222.7,224.5,226.6
XS GIS Cut Line= 4
2220093.46226511560673.3160228572219987.83764364560889.108260272
2220001.16887196561145.644426223 2220050.4742687561602.883650433
#Sta/Elev= 30
       0 2621.44    15.8 2620.39    26.6 2616.13    48.8 2618.38   111.2 2598.56
   169.1 2570.09   201.2 2534.89   225.1 2518.74   252.3 2506.11   276.4 2508.56
   304.4 2505.63   344.5 2506.13  375.182500.706   384.5 2499.26   393.62500.705
   404.5 2504.11   428.6 2502.39   464.6 2504.37   497.1 2514.41   516.8 2523.44
   573.1 2529.57   629.4 2548.36   657.6 2562.18   669.7 2565.03   681.7 2573.72
   731.9 2595.62   794.4  2626.9   919.1 2700.32   931.2 2711.04     957 2713.44
#Mann= 5 ,-1,0
       0      .1       0  375.18    .045       0   393.6      .1       0
  490.26     .06       0  587.14      .1       0
#XS Ineff= 2 , 0
                             405            2550
Permanent Ineff=
       F       F
Bank Sta=375.18,393.6
XS Rating Curve= 0 ,0
Exp/Cntr(USF)=0,0
Exp/Cntr=0.3,0.1

Type RM Length L Ch R = 1 ,9494    ,235.4,231.5,226.6
XS GIS Cut Line= 5
2220006.28745384560658.9495508172219792.88559541560890.428118453
      2219771.46      561015.2062219749.95569819561198.428407367
 2219929.8678552561606.927966356
#Sta/Elev= 30
       0  2613.2    93.7 2592.72   128.2  2578.2   175.7 2554.68   220.7 2537.42
   242.4 2518.61   258.7 2510.52   342.1 2505.34   419.1 2497.93  429.07 2494.44
   447.5 2493.18  454.192494.443   463.6 2496.92   499.8 2496.19   540.1 2499.35
   620.6 2497.72   628.9 2499.54   637.7 2504.98     657 2506.05   663.1 2509.75
   672.6 2519.16   702.5 2529.03   738.2 2536.62   760.2 2543.84   790.6 2559.47
   803.8  2562.4   945.3  2615.9  1026.7 2664.59  1052.9 2673.81  1072.3 2678.08
#Mann= 7 ,-1,0
       0      .1       0  429.07    .045       0  454.19      .1       0
  471.44     .06       0  571.44      .1       0  665.92     .06       0
  775.92      .1       0
Bank Sta=429.07,454.19
XS Rating Curve= 0 ,0
Exp/Cntr=0.3,0.1

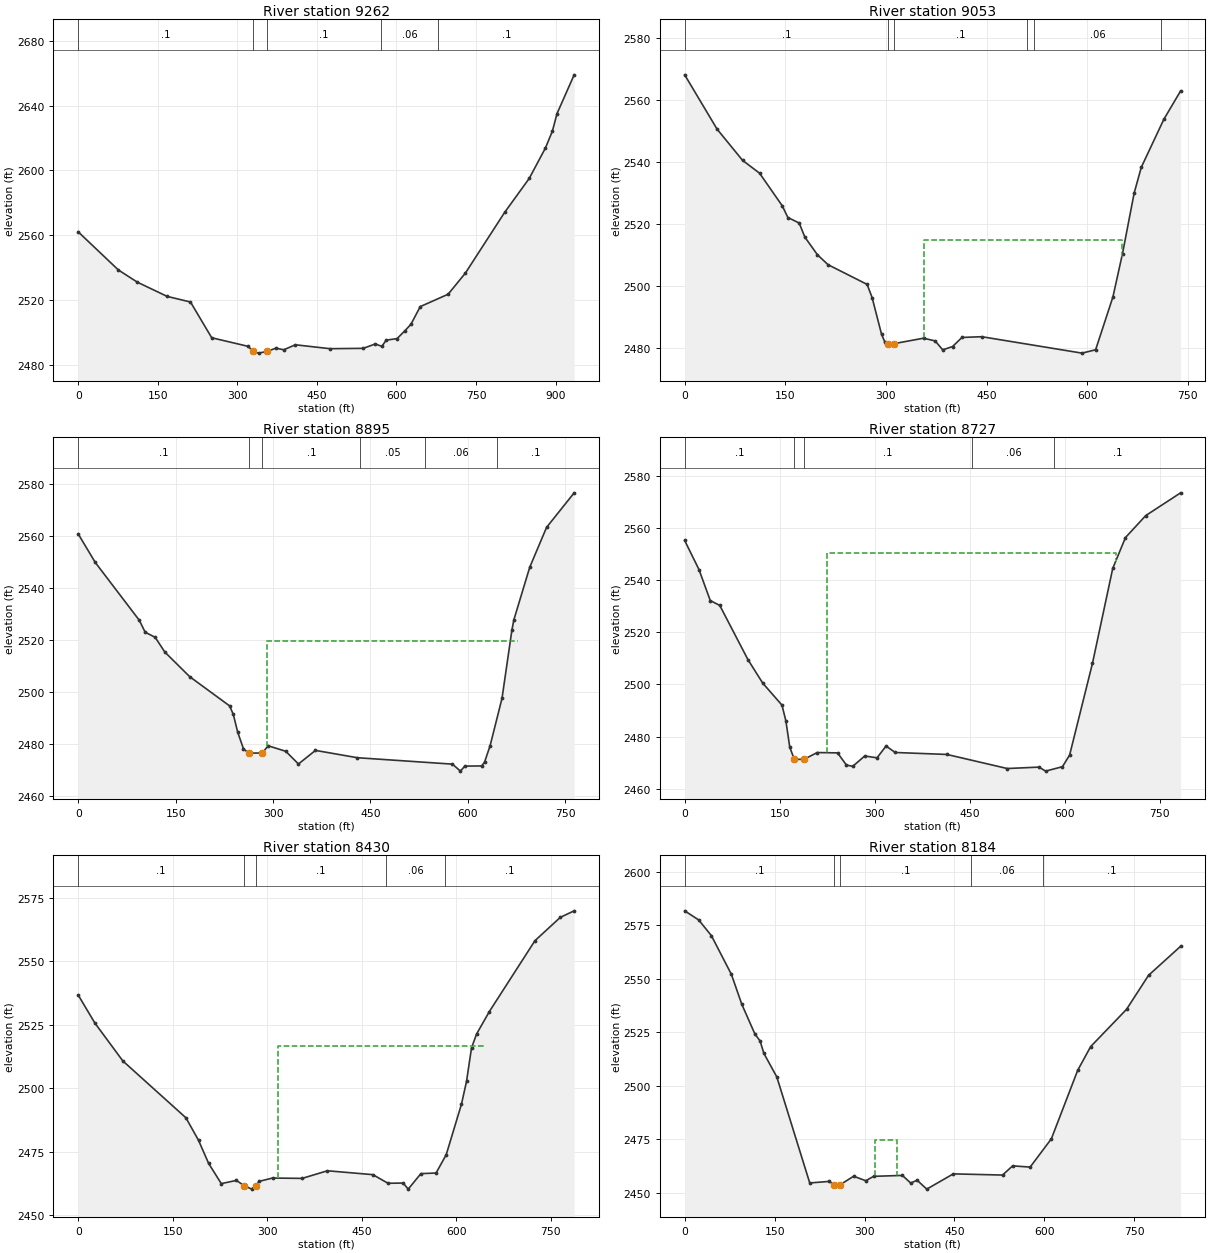
Type RM Length L Ch R = 1 ,9262    ,202.7,209.6,218.1
XS GIS Cut Line= 4
2219542.74965524560673.4937688932219540.49008103560994.267563302
2219594.79933626561267.2819822942219459.30423356561574.740197375
#Sta/Elev= 30
       0 2562.11    75.7 2538.59   111.7 2531.01   167.7 2522.27   211.7  2518.8
   251.7 2496.74   319.7 2491.49  330.412488.344     340 2487.25  356.832488.343
   372.7 2490.33   387.6 2489.32   409.4  2492.4   474.7 2489.99   537.3  2490.2
   560.3 2492.92   572.5 2491.42   580.7 2495.26   601.2 2496.22   615.6 2500.93
   627.4 2505.08   644.9 2515.97   697.4 2523.59     730 2536.65     804 2574.11
   850.4 2595.11     881  2613.9   894.1 2624.33   902.8 2635.11   935.1 2659.05
#Mann= 5 ,-1,0
       0      .1       0  330.41    .045       0  356.83      .1       0
  570.78     .06       0  679.15      .1       0
Bank Sta=330.41,356.83
XS Rating Curve= 0 ,0
Exp/Cntr(USF)=0,0
Exp/Cntr=0.3,0.1

Type RM Length L Ch R = 1 ,9053    ,154.5,157.5,162
XS GIS Cut Line= 4
2219452.86776389560675.3301312212219360.66330215560950.779272443
2219176.91061974561224.2119649912219130.36668976561334.082597082
#Sta/Elev= 30
       0 2568.17    48.3 2550.67    86.3 2540.61   111.6 2536.48   145.4 2525.98
   153.8  2522.2   170.7 2520.42   179.1 2515.88   197.9 2510.19   213.7 2506.99
   271.9 2500.65   279.4 2496.38   293.4 2484.61   298.2 2482.13     303 2481.56
   312.2 2481.56     356 2483.31   373.3 2482.44   384.6 2479.56   399.2 2480.61
   413.3 2483.55   442.8 2483.79   592.2  2478.5   612.5 2479.58   638.3  2496.6
   652.6  2510.6     670 2530.12   680.6 2538.38   714.1  2553.8   739.2 2562.99
#Mann= 6 ,-1,0
       0      .1       0     303    .045       0   312.2      .1       0
  510.47     .05       0  520.47     .06       0  709.91      .1       0
#XS Ineff= 1 ,-1
  357.01  651.37 2515.09
Permanent Ineff=
       F
Bank Sta=303,312.2
XS Rating Curve= 0 ,0
Exp/Cntr=0.3,0.1

Type RM Length L Ch R = 1 ,8895    ,169.4,168.2,163.4
XS GIS Cut Line= 4
2219377.36305095560630.0626009562219265.41300017560841.359054426
2219105.89917614560935.8840723942218973.63909524561248.266283884
#Sta/Elev= 30
       0 2560.91    26.2 2549.96    94.1 2527.67   103.1  2523.1   118.6 2521.11
   133.4 2515.45   171.8 2505.96   233.2 2494.73   238.9 2491.43   245.7 2484.55
   254.5 2478.26   262.3 2476.56   283.7 2476.61   292.4  2479.4   319.6 2477.27
   339.2 2472.38   365.4 2477.61   429.9 2474.79   576.4 2472.32   588.6 2469.63
   595.4 2471.56   621.4 2471.63   625.8 2473.09   634.4 2479.45   652.7 2497.64
   667.9 2523.85     671 2527.91   695.4 2548.09   721.3 2563.43   763.8 2576.73
#Mann= 6 ,-1,0
       0      .1       0   262.3    .045       0   283.7      .1       0
  434.54     .05       0  534.54     .06       0  644.54      .1       0
#XS Ineff= 1 ,-1
  291.44   677.6 2519.84
Permanent Ineff=
       F
Bank Sta=262.3,283.7
XS Rating Curve= 0 ,0
Exp/Cntr(USF)=0,0
Exp/Cntr=0.3,0.1

Type RM Length L Ch R = 1 ,8727    ,298.1,297.2,290.5
XS GIS Cut Line= 4
2219283.31557606560574.120818915 2219179.8947733 560688.35171968
2218937.13417164561055.3206259622218924.69677521561244.070838146
#Sta/Elev= 30
       0 2555.24    22.6 2544.08    40.4  2532.2    55.4 2530.33     100  2509.5
   123.3 2500.52   153.7 2492.07   159.9 2485.96     166 2475.91  173.222471.244
   188.7 2471.31   209.3 2473.89   241.4 2473.76   255.5 2469.09   265.4  2468.6
   284.4 2472.57   303.8 2471.86   318.1 2476.39   332.5 2473.91   414.1 2473.16
   509.5 2467.76   559.6  2468.3   570.1 2466.76   596.7 2468.47     608 2472.94
   644.1 2508.14   676.1 2544.54   696.2 2556.36   728.2 2564.79   783.3 2573.52
#Mann= 5 ,-1,0
       0      .1       0  173.22    .045       0   188.7      .1       0
  454.09     .06       0  584.09      .1       0
#XS Ineff= 1 ,-1
  224.41  680.51 2550.55
Permanent Ineff=
       F
Bank Sta=173.22,188.7
XS Rating Curve= 0 ,0
Exp/Cntr(USF)=0,0
Exp/Cntr=0.3,0.1

Type RM Length L Ch R = 1 ,8430    ,247.1,246.2,244.6
XS GIS Cut Line= 4
2218900.86801773560458.4286115312218891.34229468560676.845664961
2218869.81629545560998.7397180362218895.76409643 561243.04290589
#Sta/Elev= 30
       0 2536.66    26.3 2525.71    70.8 2510.76   170.9 2488.41   190.9 2479.55
   206.9 2470.49     227 2462.53     251 2463.78  263.492461.673   275.1  2460.4
  281.52 2461.64   287.1 2463.41   308.3 2464.72   355.3 2464.58   395.4 2467.58
   467.5 2466.05   491.6 2462.66   515.6 2462.75   523.6 2460.36   543.7 2466.45
   567.8 2466.69   583.9 2473.89   608.1 2493.76   616.1 2502.69   624.1 2515.95
   632.2  2521.4   652.3 2530.16   724.7 2558.04   764.9 2567.21   786.9 2569.78
#Mann= 5 ,-1,0
       0      .1       0  263.49    .045       0  281.52      .1       0
  488.62     .06       0  581.24      .1       0
#XS Ineff= 1 ,-1
  316.21  644.08 2516.68
Permanent Ineff=
       F
Bank Sta=263.49,281.52
XS Rating Curve= 0 ,0
Exp/Cntr=0.3,0.1

Type RM Length L Ch R = 1 ,8184    ,264.1,258.9,253.6
XS GIS Cut Line= 4
2218552.51156315560486.1150538272218634.98625575560672.744836394
2218681.21384956560921.2947158622218863.37369491 561243.72537032
#Sta/Elev= 30
       0  2581.8    23.3 2577.56    44.5 2570.22    77.9 2552.11    95.2 2538.17
   117.1 2524.23   125.8 2520.95     132 2515.23   153.7 2504.12   208.6 2454.58
   241.1  2455.3   249.2 2453.69  259.182453.732   281.8 2457.71   302.1 2455.62
   315.2 2457.67   363.2  2458.1     377 2454.51   387.6 2455.87   403.8 2451.69
     448 2458.82   530.2 2458.27     547 2462.57   576.2 2461.99   611.6 2475.22
   655.6 2507.28   677.2 2518.34     737 2535.75   773.7 2551.65   827.2 2565.23
#Mann= 5 ,-1,0
       0      .1       0   249.2    .045       0  259.18      .1       0
  476.85     .06       0  596.85      .1       0
#XS Ineff= 1 ,-1
  316.94  353.37 2474.62
Permanent Ineff=
       F
Bank Sta=249.2,259.18
XS Rating Curve= 0 ,0
Exp/Cntr(USF)=0,0
Exp/Cntr=0.3,0.1

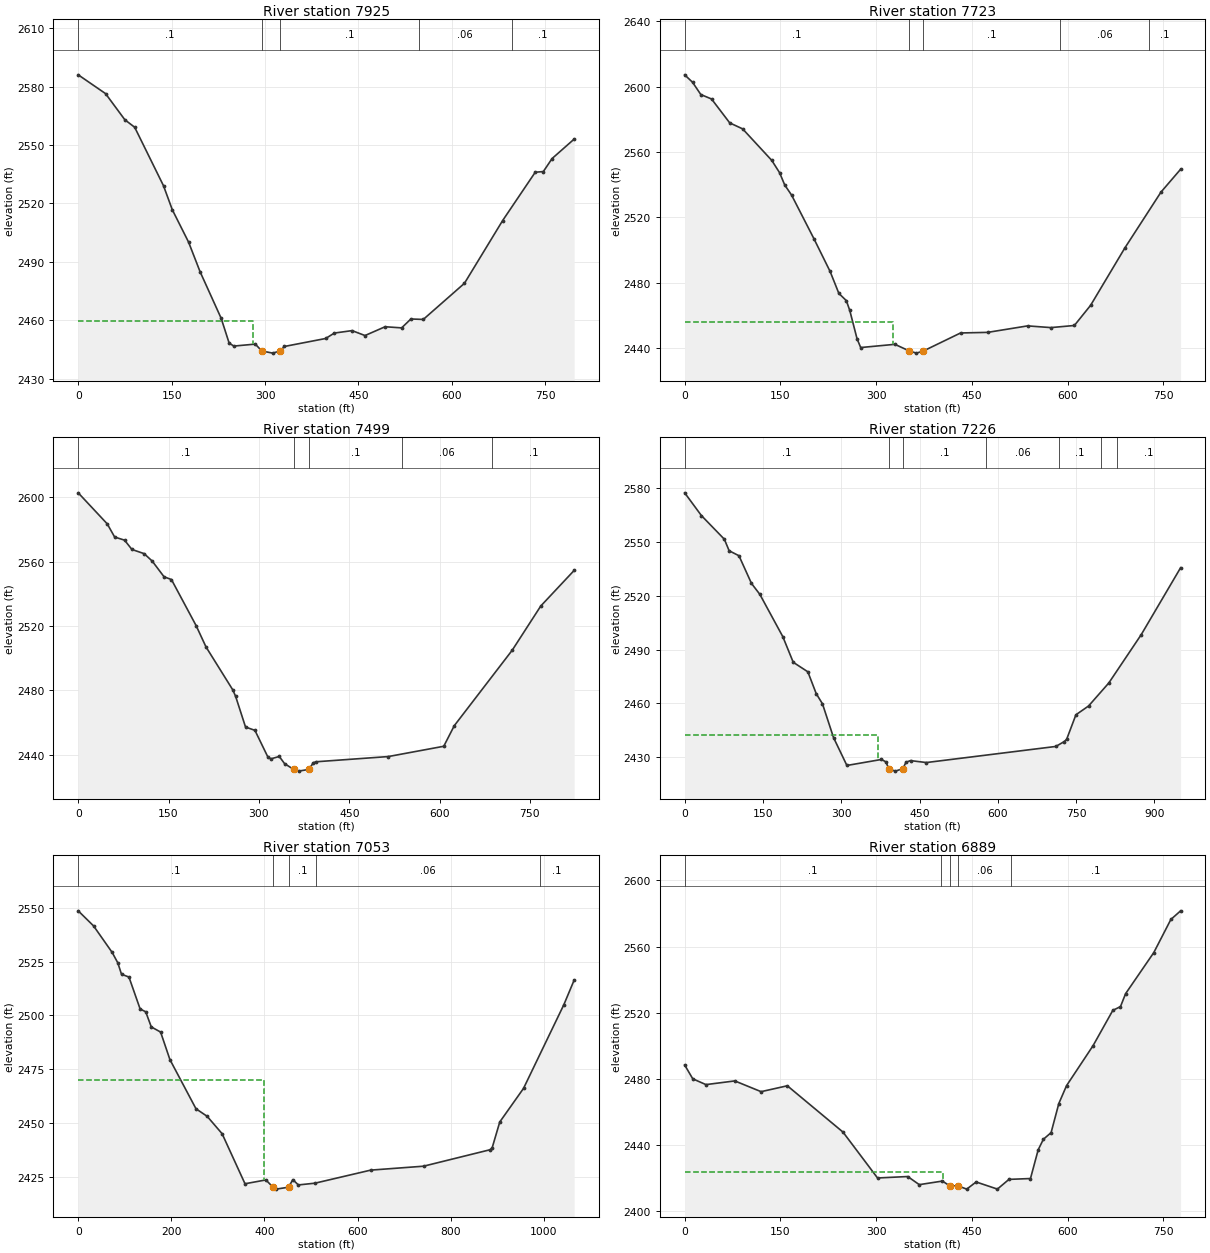
Type RM Length L Ch R = 1 ,7925    ,197,201.6,206
XS GIS Cut Line= 4
2218267.88656177560693.6462519762218424.07357993560878.865795963
2218547.80850201560953.0290080582218817.30470224561262.023898446
#Sta/Elev= 30
       0    2586    43.9 2576.36    74.9 2562.94    90.7 2559.09     137 2529.06
   151.1 2516.77   177.3 2500.11   195.7 2484.97   229.6 2461.05   242.4 2448.32
   249.9  2446.8   284.4 2447.81  294.85 2444.29   312.4 2443.18  324.272444.289
     331 2446.59   397.4 2450.69   411.4 2453.48   439.8 2454.73   460.6 2452.21
   492.9 2456.72   519.4 2456.14   534.3  2460.7   554.2 2460.47   620.3 2479.01
   681.7 2511.24     734 2536.01     747 2536.36   761.1 2543.05   796.5 2553.02
#Mann= 5 ,-1,0
       0      .1       0  294.85    .045       0  324.27      .1       0
  546.54     .06       0  696.54      .1       0
#XS Ineff= 2 , 0
          280.87 2459.82
Permanent Ineff=
       F       F
Bank Sta=294.85,324.27
XS Rating Curve= 0 ,0
Exp/Cntr=0.3,0.1

Type RM Length L Ch R = 1 ,7723    ,223.6,224.4,226.3
XS GIS Cut Line= 4
2218132.58080627560781.6734938682218299.46116049560995.076594232
2218383.67028622561103.1072820712218637.43560514561371.291075651
#Sta/Elev= 30
       0 2607.19    12.3 2602.64    25.3 2595.12    42.1  2592.4    70.6 2577.76
    90.8 2574.11   136.5 2554.79   148.7 2547.28   156.8 2539.73   167.5 2533.57
   202.5 2506.88   227.9  2486.8   241.6 2473.38   253.3 2468.96   258.7 2462.93
   270.1 2445.59   275.8 2440.24   329.4 2442.21  351.942438.156   363.2 2436.82
  374.152438.154   432.3 2449.16   474.8 2449.53   537.4  2453.5   573.8 2452.45
   610.6 2453.74   636.1 2466.11   689.8 2501.26   746.4 2535.44   777.1 2549.39
#Mann= 5 ,-1,0
       0      .1       0  351.94    .045       0  374.15      .1       0
  587.88     .06       0  727.88      .1       0
#XS Ineff= 2 , 0
          326.42 2455.81
Permanent Ineff=
       F       F
Bank Sta=351.94,374.15
XS Rating Curve= 0 ,0
Exp/Cntr(USF)=0,0
Exp/Cntr=0.3,0.1

Type RM Length L Ch R = 1 ,7499    ,271.3,272.6,275.9
XS GIS Cut Line= 5
2218064.39546871560830.1628476552218133.94417108561138.164243874
     2218158.959      561176.0212218212.98709504561267.931487883
2218448.93813521561534.070362296
#Sta/Elev= 30
       0 2602.89    48.2 2583.58    60.5 2575.39    76.9 2573.46    89.2 2567.66
   109.4 2565.08   122.8 2560.47   142.5 2550.68   154.8 2548.95   195.8 2520.27
   212.2 2507.03   256.6 2480.36   261.4 2476.26   277.8 2457.22   293.4 2455.18
   314.7 2438.74   319.8 2437.43   333.8 2438.94   342.6 2434.48  357.662430.886
   365.8 2429.81  383.162430.885   390.3 2435.03     395 2435.63   514.8 2438.87
   606.9 2445.27   624.4 2458.08   720.7 2505.07     768 2532.51   823.4 2554.63
#Mann= 5 ,-1,0
       0      .1       0  357.66    .045       0  383.16      .1       0
  537.75     .06       0  687.75      .1       0
Bank Sta=357.66,383.16
XS Rating Curve= 0 ,0
Exp/Cntr=0.3,0.1

Type RM Length L Ch R = 1 ,7226    ,173.8,173.1,166.6
XS GIS Cut Line= 4
2217886.92709992560917.1472990782217887.04751731561220.026525116
2217953.28437671561392.2423595612218367.83999787561597.981341309
#Sta/Elev= 30
       0 2577.42      32 2564.75      76 2551.53    85.2  2545.1     104 2542.32
     128 2526.87     144 2520.77     188 2497.18     208 2482.87     236 2477.55
     252 2465.39     264 2459.69   285.2 2440.86   310.8  2425.3     377 2428.65
   385.5  2427.3  391.052423.508   403.7 2422.14  417.892423.508   424.1 2427.11
   432.7 2428.01   463.1 2426.93   711.1 2435.91   727.3 2438.64   731.8 2439.87
   749.6 2453.58   773.8 2458.48   812.6 2471.32   874.7 2498.28   950.2 2535.64
#Mann= 7 ,-1,0
       0      .1       0  391.05    .045       0  417.89      .1       0
  577.39     .06       0  717.39      .1       0  797.39     .06       0
  827.39      .1       0
#XS Ineff= 2 , 0
          370.52 2442.54
Permanent Ineff=
       F       F
Bank Sta=391.05,417.89
XS Rating Curve= 0 ,0
Exp/Cntr(USF)=0,0
Exp/Cntr=0.3,0.1

Type RM Length L Ch R = 1 ,7053    ,163.4,164.2,165.5
XS GIS Cut Line= 4
2217726.40561013560952.2121478022217717.92817928561302.934317027
2217806.34195322561438.5304211152218331.59855502561610.476095884
#Sta/Elev= 30
       0 2548.66      33 2541.64      73 2529.28      85 2524.48      93 2519.15
     109 2517.85     133    2503     145 2501.68     157 2494.64     177 2492.25
     197 2479.44     253 2456.56     277 2453.05   309.1 2444.96   358.3 2421.67
   403.2 2423.45  418.442420.067   425.1 2419.17  452.022420.065     461 2423.59
   472.9 2421.12   508.7 2421.94   628.3 2428.01   741.9 2429.84     885 2437.51
   889.2 2438.34   905.6 2450.42   956.6 2466.03  1043.3 2504.99  1065.4 2516.44
#Mann= 5 ,-1,0
       0      .1       0  418.44    .045       0  452.02      .1       0
  510.82     .06       0   992.7      .1       0
#XS Ineff= 2 , 0
             400    2470
Permanent Ineff=
       F       F
Bank Sta=418.44,452.02
XS Rating Curve= 0 ,0
Exp/Cntr=0.3,0.1

Type RM Length L Ch R = 1 ,6889    ,296,297.5,298.4
XS GIS Cut Line= 6
2217498.64357742 561056.831807732217540.35947164561229.722096464
2217582.36146469561376.8993025632217671.75854887561544.418162997
2217685.95659829561649.4256643482217698.91711049561799.004489495
#Sta/Elev= 30
       0 2488.29    12.7 2479.92    33.3 2476.43    78.5 2478.66   119.7 2472.16
   160.8 2475.72     248  2447.7   302.1 2419.93   349.4  2420.8   367.5 2415.89
   403.8 2418.06   415.2 2415.14   428.2 2415.16   441.8 2413.18   456.6 2417.51
   489.9  2413.2     508 2419.08   541.7 2419.59   553.8    2437   561.9 2443.34
     574 2447.37   586.1 2464.98   598.2 2475.79   639.7 2499.97   670.7 2521.36
   682.7 2523.63   690.7 2531.46   734.9 2556.34   761.6 2576.36   776.9 2581.59
#Mann= 5 ,-1,0
       0      .1       0  400.91     .06       0   415.2    .045       0
   428.2     .06       0  510.91      .1       0
#XS Ineff= 2 , 0
          404.08 2423.49
Permanent Ineff=
       F       F
Bank Sta=415.2,428.2
XS Rating Curve= 0 ,0
Exp/Cntr=0.3,0.1