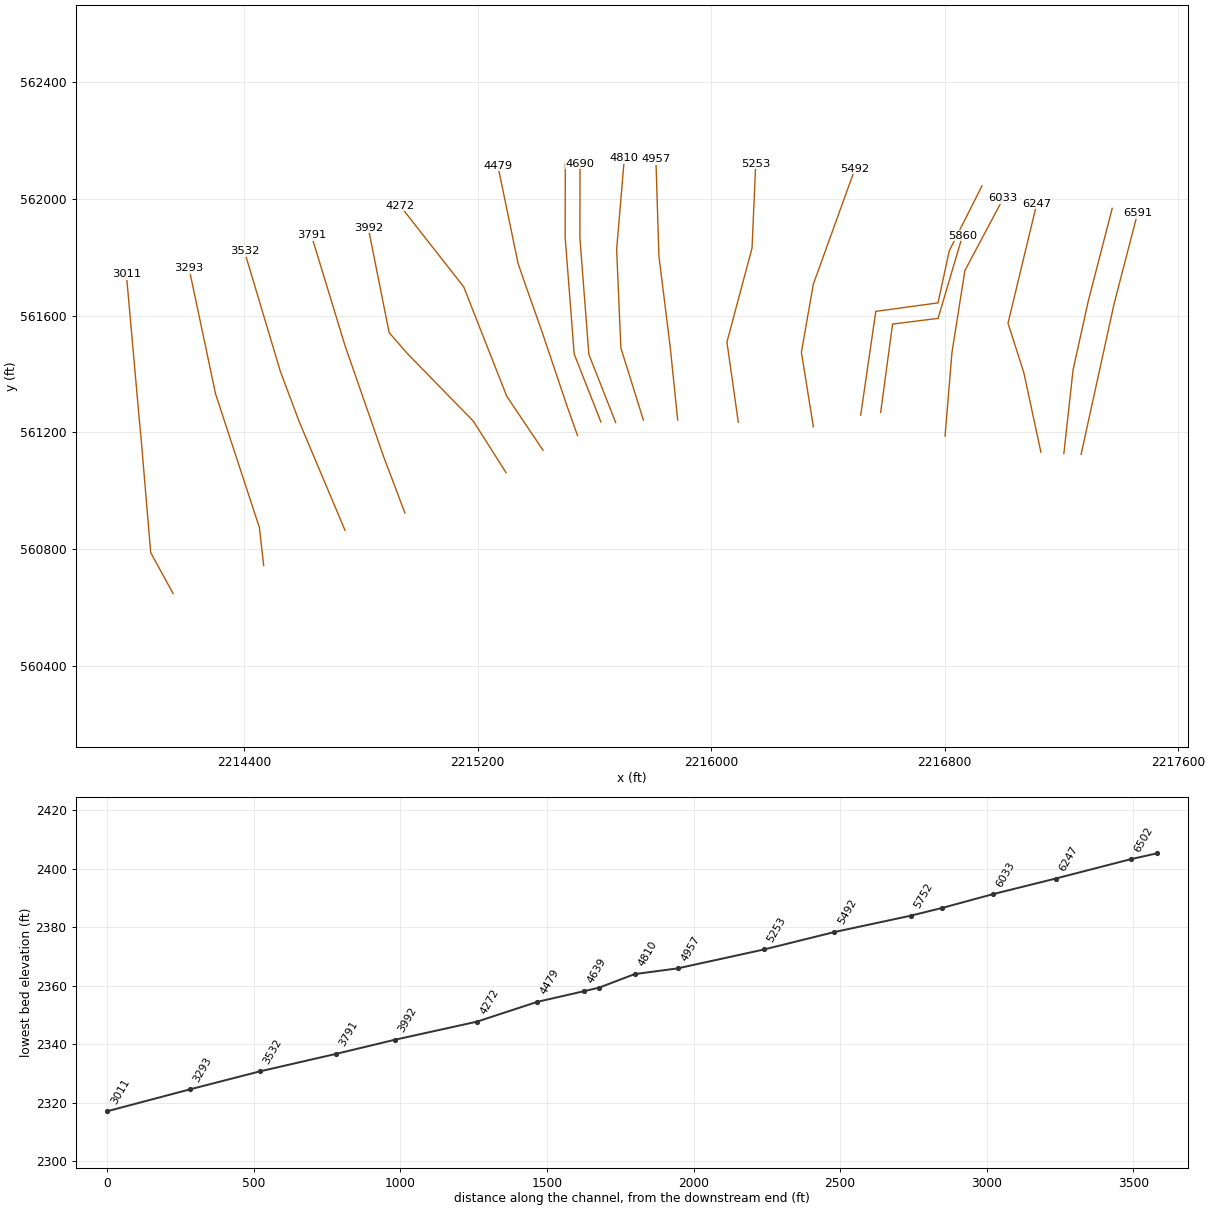
HEC-RAS study VALLEYFK.prj: VALLEYFK

--- VALLEYFK.g01 (geometry) --- (continued)

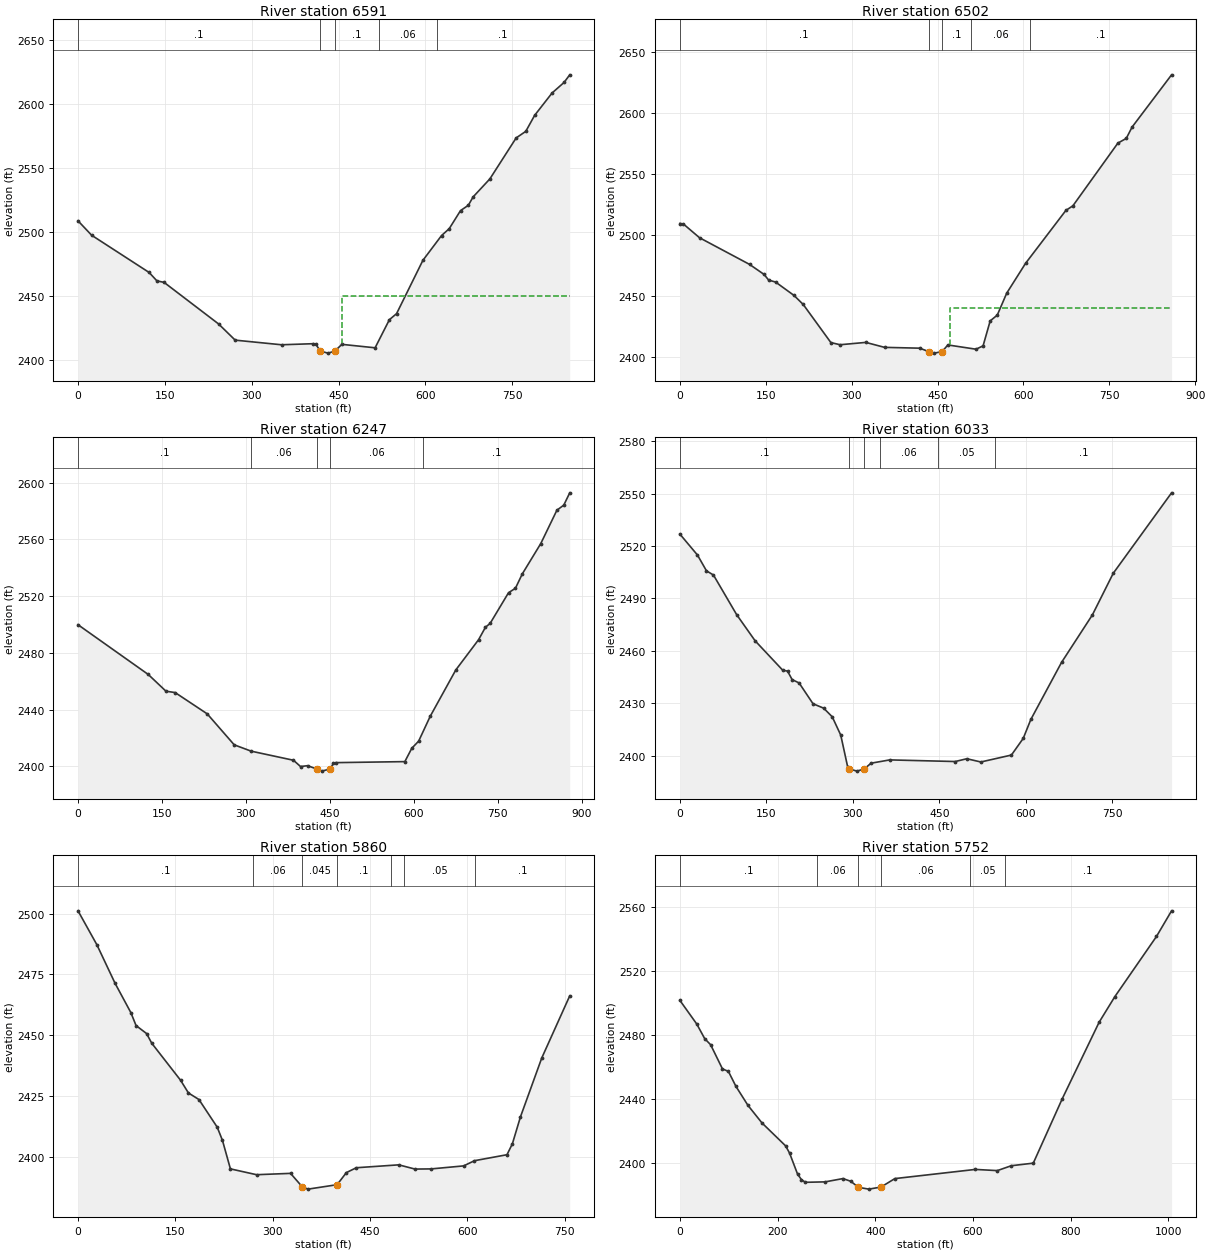
Type RM Length L Ch R = 1 ,6591    ,88.7,88.7,88.6
XS GIS Cut Line= 3
2217267.13985328561124.029175022 2217380.2944881561641.044660953
2217460.46454553561950.631746329
#Sta/Elev= 30
       0 2508.54    23.6 2497.25   122.8  2468.2   136.3 2461.62   148.6 2460.47
   242.8 2427.97   271.4 2415.34   351.4 2411.73   406.6 2412.57   410.6 2412.27
  418.32 2406.76   431.8  2405.2  443.35 2406.76   455.7 2412.05     513 2409.36
   537.7 2431.32   550.1 2436.03   595.5 2477.64   627.7    2497     641 2502.39
   660.5  2516.5     674 2520.66   682.3 2527.22   711.2 2541.27   756.6 2573.28
   773.2  2578.4   788.5  2590.9   818.6 2608.35   839.3 2616.61   849.1 2622.55
#Mann= 5 ,-1,0
       0      .1       0  418.32    .045       0  443.35      .1       0
     520     .06       0  619.25      .1       0
#XS Ineff= 2 , 0
                          455.69            2450
Permanent Ineff=
       F       F
Bank Sta=418.32,443.35
XS Rating Curve= 0 ,0
Exp/Cntr(USF)=0,0
Exp/Cntr=0.3,0.1

Type RM Length L Ch R = 1 ,6502    ,249.9,255.8,262.2
XS GIS Cut Line= 4
2217208.14257719561126.9830462722217239.69600875561414.136605611
2217291.85944575561650.3584814142217373.73885931561967.968601918
#Sta/Elev= 30
       0  2509.5     6.2  2509.1    34.4 2497.82   121.7 2475.98   147.1 2467.75
   155.1 2463.11   167.2 2461.49   199.4 2450.52   215.5  2443.1   263.8 2411.85
   279.9 2410.09   324.8 2412.01   357.5 2407.94     419 2407.27  434.282404.536
   444.7 2403.21  458.192404.537   468.1 2409.92   517.3 2406.42   529.6 2409.18
     542 2429.62   554.4  2434.4   570.9  2452.4   603.9 2476.91   674.2 2520.23
   686.5 2524.03     765  2575.4   779.7 2579.29   789.8 2588.55   858.8 2631.41
#Mann= 5 ,-1,0
       0      .1       0  434.28    .045       0  458.19      .1       0
  508.88     .06       0  610.79      .1       0
#XS Ineff= 2 , 0
                          472.24            2440
Permanent Ineff=
       F       F
Bank Sta=434.28,458.19
XS Rating Curve= 0 ,0
Exp/Cntr=0.3,0.1

Type RM Length L Ch R = 1 ,6247    ,216,214,203.5
XS GIS Cut Line= 4
2217129.53011109561131.5623548432217070.98252311561404.382043193
2217016.89545061561573.9177613322217115.22663518561983.461557772
#Sta/Elev= 30
       0 2499.88   125.4 2464.81   157.1 2452.99   173.5 2452.02   230.8    2437
     279 2415.15   309.3 2410.69   384.8 2404.28   397.4 2399.86     410 2400.45
  426.632398.076   435.2 2396.61  450.152398.077   456.2 2402.12   460.3  2402.6
   583.7 2403.32   596.1 2412.72   608.4 2417.78     629 2435.27   674.7 2467.96
   715.4 2489.31   727.7 2498.12     736 2500.79   768.9 2522.46   781.2 2525.58
   793.5 2535.73   826.5 2557.13   855.3 2580.67   867.6 2584.24   878.2 2592.91
#Mann= 5 ,-1,0
       0      .1       0  309.03     .06       0  426.63    .045       0
  450.15     .06       0  616.99      .1       0
Bank Sta=426.63,450.15
XS Rating Curve= 0 ,0
Exp/Cntr(USF)=0,0
Exp/Cntr=0.3,0.1

Type RM Length L Ch R = 1 ,6033    ,197.4,173,140.3
XS GIS Cut Line= 4
2216801.22865788561187.0962620952216824.83557703561473.091847668
2216869.17766431561754.5586178632217000.82451084562002.510313137
#Sta/Elev= 30
       0 2526.83    30.6  2514.8    46.2 2505.78    58.3 2503.39    98.4  2480.8
   130.5  2465.8   178.4 2448.97   186.7 2448.47   194.7 2443.61   206.8 2441.69
   230.9 2429.81   249.4 2427.26   264.2 2422.35     279 2411.88   291.1 2393.54
  293.642392.552   307.1 2391.28  319.782392.552   331.6 2395.82     364  2397.7
   477.4 2396.77   497.6 2398.36   521.9 2396.51   574.9 2400.47   595.4    2410
   608.6 2420.84   661.8 2453.43   715.3  2480.6   751.5 2504.41   852.6 2550.39
#Mann= 6 ,-1,0
       0      .1       0  293.64    .045       0  319.78      .1       0
  346.97     .06       0  446.97     .05       0  546.97      .1       0
Bank Sta=293.64,319.78
XS Rating Curve= 0 ,0
Exp/Cntr=0.3,0.1

Type RM Length L Ch R = 1 ,5860    ,100.9,107.8,110.2
XS GIS Cut Line= 4
2216580.72335038561268.4604493362216621.47709579561571.081834161
2216777.31455186561590.5353964472216860.97038228561873.919521989
#Sta/Elev= 30
       0 2501.19      29 2487.27    57.2 2471.31    81.4 2459.31    89.5 2453.93
   105.7 2450.65   113.7 2446.65   158.1 2431.42   170.2 2426.18   186.4 2423.48
   214.6 2412.08   222.7 2406.61   234.9 2394.92   275.2 2392.52   327.6 2393.07
   345.5 2387.57   354.6 2386.58   399.42388.411   413.6 2393.38     429 2395.39
   494.4 2396.58   519.4 2394.84   544.4 2394.91   594.4 2396.15   611.1 2398.29
   661.2 2400.75   669.5 2405.25     682 2416.38   714.8  2440.6   757.9 2466.17
#Mann= 7 ,-1,0
       0      .1       0     270     .06       0   345.5    .045       0
   399.4      .1       0   482.4     .06       0   502.4     .05       0
   612.4      .1       0
Bank Sta=345.5,399.4
XS Rating Curve= 0 ,0
Exp/Cntr(USF)=0,0
Exp/Cntr=0.3,0.1

Type RM Length L Ch R = 1 ,5752    ,233.5,259.5,277.7
XS GIS Cut Line= 5
2216512.33287705561258.8448118282216564.05678434561614.579749094
2216777.09281338561643.6834918892216815.74909417561822.621846725
2216927.65345308562044.800889402
#Sta/Elev= 30
       0 2501.89    34.7 2487.04    50.9 2477.93      63 2474.14    87.2 2459.04
    99.4 2457.47   114.8 2448.12   139.5  2436.2   168.1 2425.27   216.6  2410.9
   224.7 2406.32   240.8 2393.39   248.9 2389.81     257 2388.18   297.4 2388.46
   333.8 2390.51     350  2388.8   365.4 2385.03   386.8 2383.92   411.6 2385.21
     440  2390.5   604.7 2396.23   649.7 2395.49   678.3 2398.54   723.3 2400.15
   782.8 2440.52   858.1 2488.23   890.3 2504.23   975.4 2541.78  1006.3  2557.8
#Mann= 6 ,-1,0
       0      .1       0     280     .06       0   365.4    .045       0
   411.6     .06       0  594.49     .05       0  664.49      .1       0
Bank Sta=365.4,411.6
XS Rating Curve= 0 ,0
Exp/Cntr(USF)=0,0
Exp/Cntr=0.3,0.1

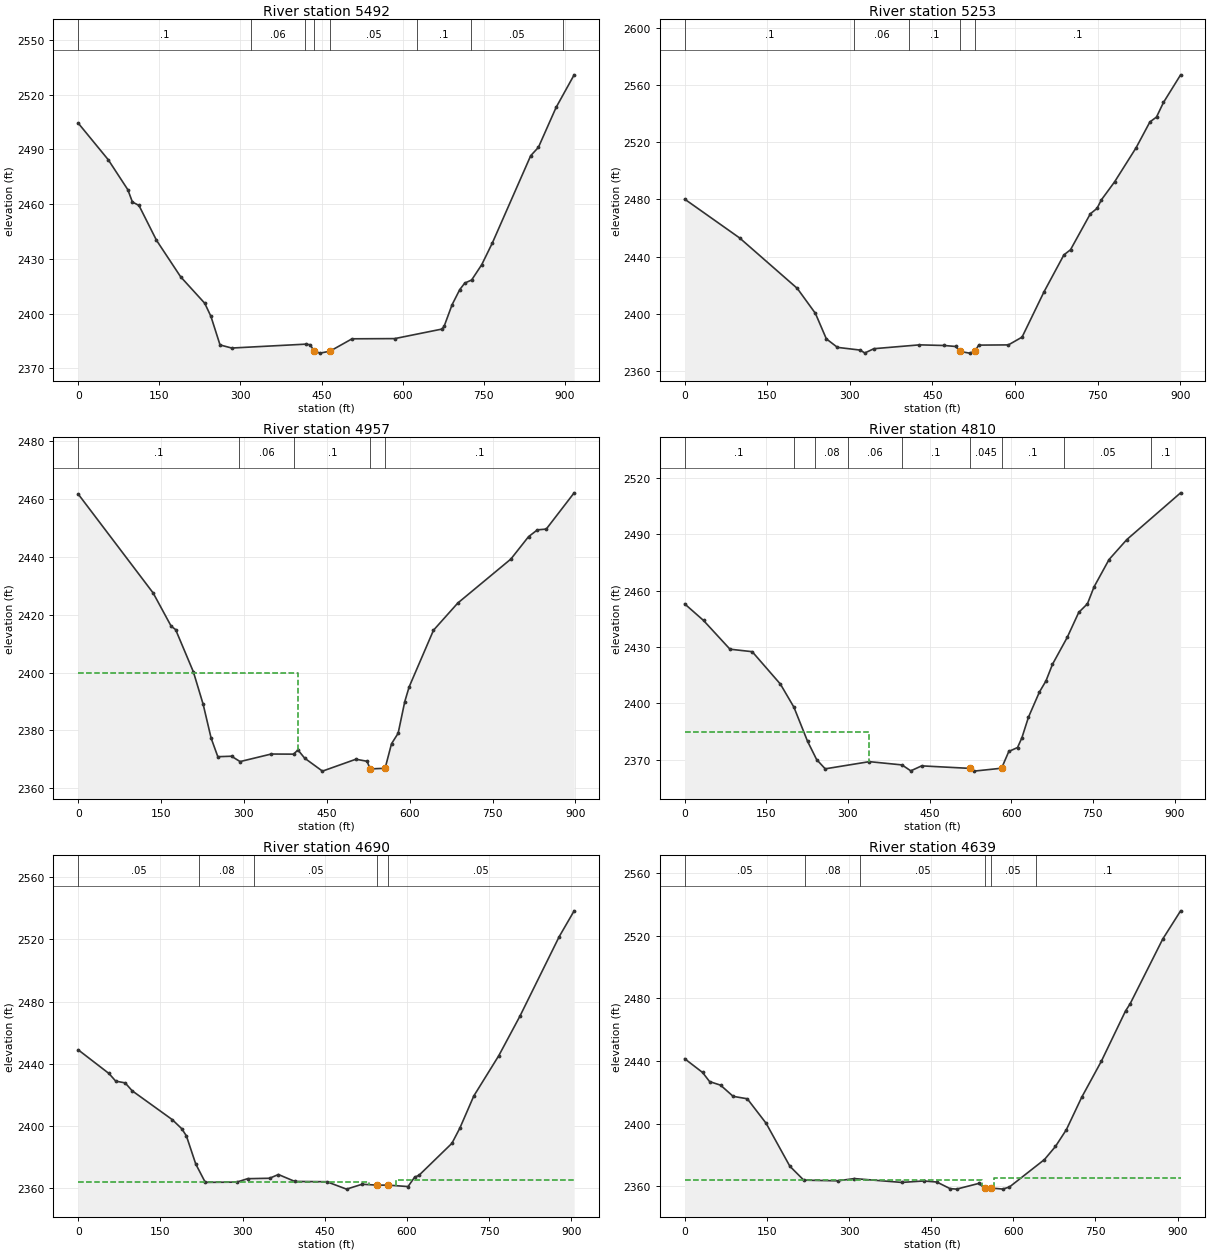
Type RM Length L Ch R = 1 ,5492    ,240.8,239.7,238
XS GIS Cut Line= 4
2216350.27715188 561218.25974309 2216309.1986139561474.289398223
2216350.00142662561707.5787259012216492.70839353562103.409517986
#Sta/Elev= 30
       0 2504.43    55.6 2484.33    91.7 2467.94   100.2 2461.17   112.3 2459.31
   144.7 2440.22   189.4 2420.18   233.9  2405.7   245.3 2398.55   262.2 2382.84
   283.8 2381.14   420.6 2383.27   428.7 2382.95  436.292379.462   447.6 2378.35
  465.732379.462   506.3  2386.2   585.1 2386.31   672.2 2391.52   676.4 2392.98
   691.2 2404.87   705.4 2413.18   714.7 2416.75   727.4 2418.45     746 2426.82
   765.7 2438.76   836.6 2486.59   850.8 2491.14   883.5 2513.02   916.9  2530.9
#Mann= 8 ,-1,0
       0      .1       0   319.3     .06       0   419.3     .05       0
  436.29    .045       0  465.73     .05       0  626.13      .1       0
  726.13     .05       0  896.13      .1       0
Bank Sta=436.29,465.73
XS Rating Curve= 0 ,0
Exp/Cntr=0.3,0.1

Type RM Length L Ch R = 1 ,5253    ,292.7,295.8,303
XS GIS Cut Line= 4
2216093.13611165561234.4688736952216054.16607792561509.181477925
2216140.13235308561831.4411443262216152.76336475 562121.00327297
#Sta/Elev= 30
       0 2480.19    99.7 2453.05   204.5 2417.73   237.5  2400.2   257.3  2382.4
   277.5 2376.44   318.9 2374.53   327.1  2372.5   343.7 2375.51   426.5  2378.2
   471.5 2377.75   492.7 2377.05  499.67  2373.6   517.4 2372.41  526.96 2373.69
   534.1 2378.02     588 2378.17   612.8 2383.62   652.8  2415.4   688.8 2441.17
   700.8 2444.76   736.8 2469.91   748.9  2473.7   756.9  2479.7   780.9  2492.3
   819.9 2516.13     845 2534.22     857 2537.64   869.7 2547.88   900.8 2567.19
#Mann= 5 ,-1,0
       0      .1       0  307.46     .06       0  407.46      .1       0
  499.67    .045       0  526.96      .1       0
Bank Sta=499.67,526.96
XS Rating Curve= 0 ,0
Exp/Cntr(USF)=0,0
Exp/Cntr=0.3,0.1

Type RM Length L Ch R = 1 ,4957    ,147,146.3,146.9
XS GIS Cut Line= 4
2215885.51160743561241.7917512682215859.99880986561491.918586342
2215821.26902193561803.7594772022215810.89220064562135.631251796
#Sta/Elev= 30
       0 2461.69   135.7 2427.49   168.3 2416.01   176.3 2414.85   208.5 2400.23
   226.2    2389   240.6 2377.32   252.7 2370.92   277.5 2371.08     293 2369.23
   349.4 2371.84   389.7  2371.8   397.8 2373.24   409.9 2370.41   442.1 2365.93
   502.6 2370.04   522.8 2369.34   528.5 2366.69  555.512366.921   567.1 2375.39
   579.1 2379.02   591.1 2389.96     599 2395.04   643.1 2414.63   687.1 2424.03
   783.2 2439.24   815.2 2446.98   831.2 2449.32   847.2 2449.59   897.7 2462.12
#Mann= 5 ,-1,0
       0      .1       0  291.42     .06       0  391.42      .1       0
   528.5    .045       0  555.51      .1       0
#XS Ineff= 2 , 0
           397.8    2400
Permanent Ineff=
       F       F
Bank Sta=528.5,555.51
XS Rating Curve= 0 ,0
Exp/Cntr=0.3,0.1

Type RM Length L Ch R = 1 ,4810    ,121.1,120.8,124.3
BEGIN DESCRIPTION:
structure xs 4
END DESCRIPTION:
XS GIS Cut Line= 4
2215768.09526419561241.7325831522215690.86435816561489.325781882
2215676.43257975561827.1918311012215702.81132142562139.790303384
#Sta/Elev= 30
       0  2452.9    34.6 2444.09    83.2 2428.81   124.1 2427.48   175.9 2410.24
   200.7 2397.97   225.7 2379.88   242.4 2370.15   258.2  2365.2   339.3 2369.02
   399.3 2367.28   415.4 2364.13   435.4 2366.78   523.5 2365.45   531.5 2363.98
  582.242365.525   595.5 2374.43   611.6 2376.54   619.6 2381.73   631.6 2392.63
   651.7    2406   663.8 2411.94   675.8  2420.8   702.8 2435.05     724 2448.36
     740 2452.95   752.1 2461.92   779.7 2476.48   812.3 2487.07   911.2 2511.94
#Mann= 9 ,-1,0
       0      .1       0     200     .06       0     240     .08       0
  299.36     .06       0  399.36      .1       0   523.5    .045       0
  582.24      .1       0  697.53     .05       0  857.53      .1       0
#XS Ineff= 2 , 0
          338.59    2385
Permanent Ineff=
       F       F
Bank Sta=523.5,582.24
XS Rating Curve= 0 ,0
Exp/Cntr(USF)=0,0
Exp/Cntr=0.3,0.1

Type RM Length L Ch R = 1 ,4690    ,50.8,50.3,50.2
BEGIN DESCRIPTION:
structure xs 3
END DESCRIPTION:
XS GIS Cut Line= 4
2215673.07812077561233.3869431422215581.36726523561466.954863299
2215550.49642606561867.0255470392215551.07323608562120.383193266
#Sta/Elev= 30
       0 2448.94    56.1 2433.73    68.5 2428.82    85.7 2427.68    98.6 2422.58
   171.7 2404.06   188.9 2398.27   197.5 2393.63   214.6 2375.53     232 2363.71
   289.3 2363.86   309.3 2366.08   349.4 2366.36   365.5 2368.77   395.5 2364.32
   453.8 2364.13   489.9 2359.37   518.5 2362.52  545.072361.937   566.1 2361.95
   602.2 2361.01   614.2 2367.04   622.3 2368.29   682.3 2388.82   696.8 2398.61
   722.3 2419.29   767.8 2445.15   806.3 2470.46   878.3 2521.79   905.5 2538.32
#Mann= 5 ,-1,0
       0     .05       0     220     .08       0  320.93     .05       0
  545.07    .045       0   566.1     .05       0
#XS Ineff= 2 , 0
          530.07  2363.7   581.1            2365
Permanent Ineff=
       F       F
Bank Sta=545.07,566.1
XS Rating Curve= 0 ,0
Exp/Cntr(USF)=0,0
Exp/Cntr=0.3,0.1

Type RM Length L Ch R = 1 ,4639    ,156.9,160.3,167.7
BEGIN DESCRIPTION:
structure xs 2
END DESCRIPTION:
XS GIS Cut Line= 4
2215622.71749732561234.7877947832215531.00664178 561468.35571494
2215500.13580261 561868.426398682215500.71261263562121.784044907
#Sta/Elev= 30
       0 2441.49    32.7  2432.7    45.5 2426.89    65.5  2424.6    88.5 2417.46
   114.3  2415.9   148.7 2400.25     192 2372.83   217.4 2363.92   279.8 2363.48
   309.6 2364.92   396.2 2362.47   436.3 2363.38   460.4 2362.72   484.4 2358.52
   496.4 2358.18   536.6 2361.79   547.7  2358.9  558.86  2358.9   580.7 2358.23
   592.8  2359.5   656.9 2377.08     677 2385.45   696.9 2396.16   724.9 2416.87
   760.9 2439.98   804.9    2472   813.3 2476.58   872.9 2517.98   905.5 2535.98
#Mann= 6 ,-1,0
       0     .05       0     220     .08       0  320.93     .05       0
   547.7    .045       0  558.86     .05       0  640.93      .1       0
#XS Ineff= 2 , 0
           542.3  2363.7  564.26            2365
Permanent Ineff=
       F       F
Bank Sta=547.7,558.86
XS Rating Curve= 0 ,0
Exp/Cntr(USF)=0,0
Exp/Cntr=0.3,0.1

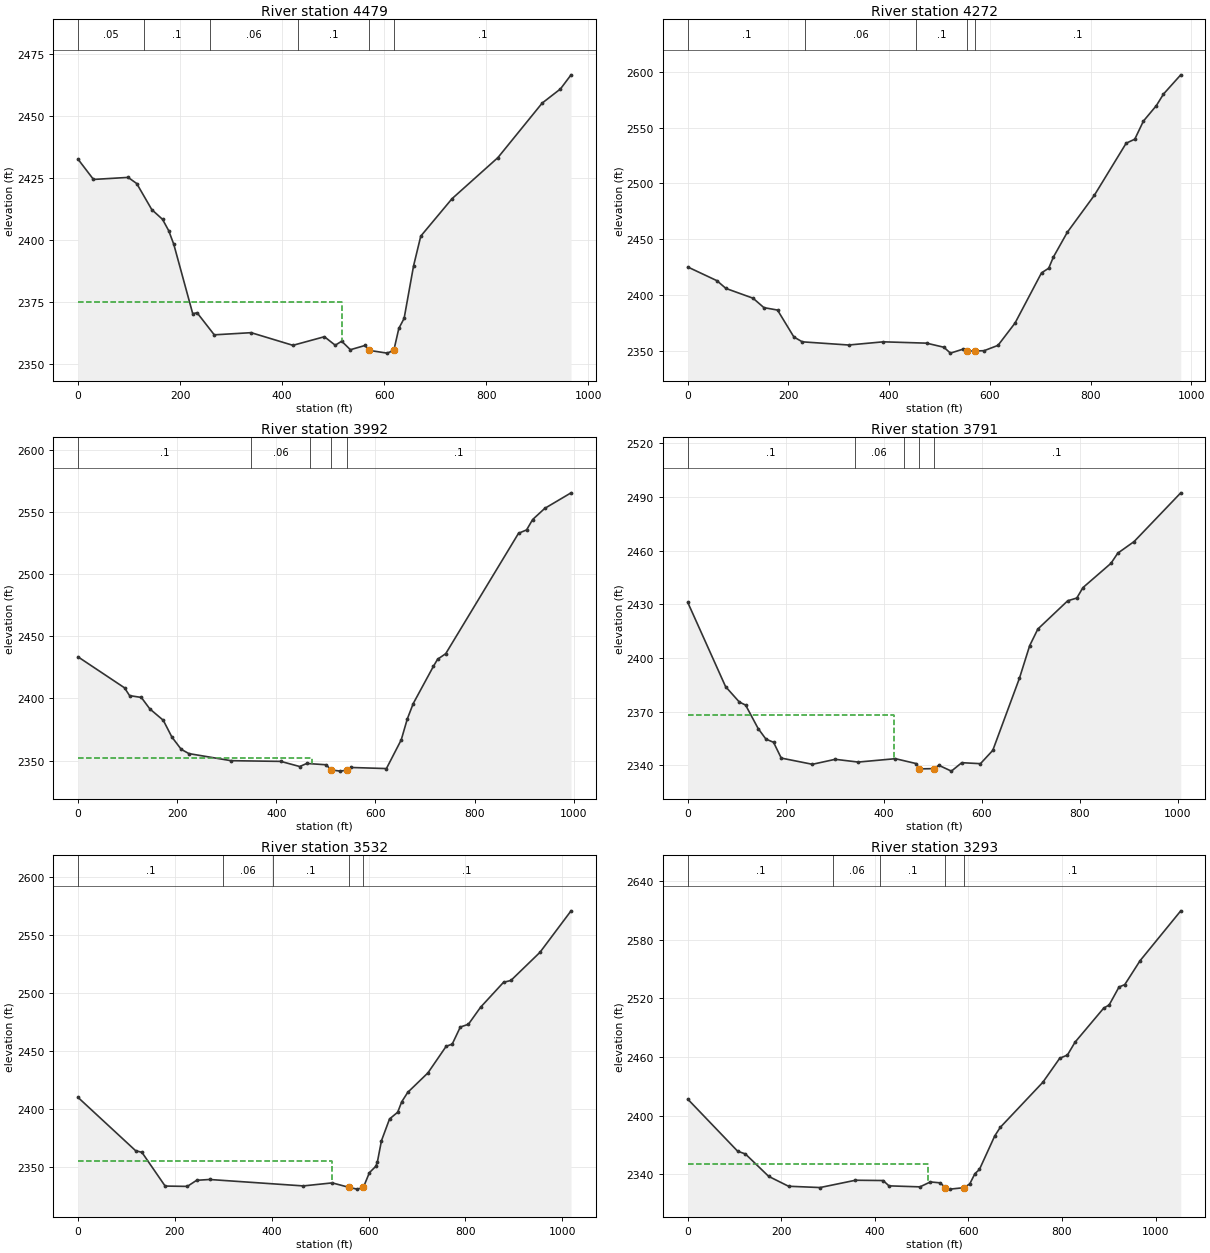
Type RM Length L Ch R = 1 ,4479    ,202.6,207.4,212.3
BEGIN DESCRIPTION:
structure xs 1
END DESCRIPTION:
XS GIS Cut Line= 6
2215542.41124282561188.7460992092215509.33843737561281.749234561
2215419.32358415561549.0880430282215363.71049724561706.698055279
2215338.83256268561779.1634496042215269.64914832562113.560071825
#Sta/Elev= 30
       0 2432.53    30.2  2424.4    98.1 2425.22   114.9 2422.76   144.5 2412.25
   165.5 2408.35   177.6 2403.79   187.6 2398.27   224.7 2370.38   233.2 2370.77
   266.9 2361.88   339.1 2362.75     421 2357.66   482.7 2361.12   503.9  2357.7
   516.6 2359.31   533.6 2355.89   562.1 2357.59  570.952355.613   605.5 2354.52
  618.712355.613   628.5 2364.45   638.9 2368.51   657.4 2389.63   671.5 2401.59
   732.8 2416.66   822.7 2433.19   909.4 2455.12   945.2 2460.81     966 2466.49
#Mann= 6 ,-1,0
       0     .05       0  128.71      .1       0  258.71     .06       0
  430.79      .1       0  570.95    .045       0  618.71      .1       0
#XS Ineff= 2 , 0
          516.63    2375
Permanent Ineff=
       F       F
Bank Sta=570.95,618.71
XS Rating Curve= 0 ,0
Exp/Cntr=0.3,0.1

Type RM Length L Ch R = 1 ,4272    ,278.4,279.9,284.3
XS GIS Cut Line= 4
2215424.38299892561138.1919734262215299.94049932561323.737975831
2215152.77477173561698.4355345132214935.17385028561976.334398714
#Sta/Elev= 30
       0 2424.96    57.8  2412.7    75.8 2405.73   129.6 2396.97   151.2 2388.51
   178.2 2386.34   210.7  2362.2   227.4 2357.85   319.5    2355   388.3 2357.86
   474.3 2356.66   508.6 2352.98   521.5 2347.72   547.3 2351.37   554.5 2349.61
   569.9 2349.61   588.4 2349.91     616 2354.68   649.8 2374.66   702.4 2419.69
   716.7 2423.86     726 2433.89   753.7 2456.14   807.3 2489.24   870.5 2535.96
   887.6 2539.56   904.7 2555.76   930.4 2569.64   944.6 2580.03   978.9 2597.27
#Mann= 5 ,-1,0
       0      .1       0  233.41     .06       0  453.41      .1       0
   554.5    .045       0   569.9      .1       0
Bank Sta=554.5,569.9
XS Rating Curve= 0 ,0
Exp/Cntr(USF)=0,0
Exp/Cntr=0.3,0.1

Type RM Length L Ch R = 1 ,3992    ,208.8,200.6,195.2
XS GIS Cut Line= 5
2215297.72241835561061.4264732972215185.80109665561237.830925019
     2214960.408      561469.1872214897.33269178561541.527948892
2214825.77768683561901.173458713
#Sta/Elev= 30
       0 2433.39    93.7 2408.53   103.9 2402.25   127.6 2400.79   144.8 2391.56
   171.9 2382.43   189.3 2368.94   208.1 2359.07   223.7 2355.62   308.5 2349.94
     409 2349.37   447.2 2345.23   461.4 2347.71     501 2346.63  509.842342.531
   529.2 2341.54   543.4 2342.41   550.5 2344.48   622.1  2343.6     652  2366.7
   664.2 2383.47   676.2 2395.89     717 2425.87   725.4 2431.53   741.7 2435.95
   888.6 2532.74   904.9 2535.48   917.1 2543.82   941.5 2552.78   994.6 2565.29
#Mann= 5 ,-1,0
       0      .1       0  348.91     .06       0  468.91      .1       0
  509.84    .045       0   543.4      .1       0
#XS Ineff= 2 , 0
          472.73 2351.73
Permanent Ineff=
       F       F
Bank Sta=509.84,543.4
XS Rating Curve= 0 ,0
Exp/Cntr=0.3,0.1

Type RM Length L Ch R = 1 ,3791    ,258.2,259.2,258.6
XS GIS Cut Line= 4
2214951.49350907560922.7614815572214880.58261174561110.219177903
2214746.21866039561496.8005490132214630.66487931561876.232919739
#Sta/Elev= 30
       0 2431.08    77.2 2383.97   105.2 2375.39   118.1 2373.65   143.7 2360.52
   159.6 2354.62   175.1 2352.85   190.8 2344.02   254.4 2340.54     301 2343.33
   347.9 2341.79   423.8 2343.68   466.1 2340.95  472.512337.967  501.912338.124
   512.7 2339.95   538.1 2336.72   559.3 2341.44   597.4 2340.89   622.6 2348.34
     677 2388.67   697.9 2406.91   714.6  2416.2   775.5    2432   794.1 2433.54
   806.6 2439.37   863.8 2452.95   877.7 2458.63   911.1 2465.14  1006.3 2492.39
#Mann= 5 ,-1,0
       0      .1       0  340.42     .06       0  440.42      .1       0
  472.51    .045       0  501.91      .1       0
#XS Ineff= 2 , 0
          421.86 2367.97
Permanent Ineff=
       F       F
Bank Sta=472.51,501.91
XS Rating Curve= 0 ,0
Exp/Cntr(USF)=0,0
Exp/Cntr=0.3,0.1

Type RM Length L Ch R = 1 ,3532    ,240.3,238.5,237.4
XS GIS Cut Line= 4
2214746.09819466560863.5952696512214589.95601056561234.538911403
 2214524.6775602561408.8105176622214401.80916294  561820.2557801
#Sta/Elev= 30
       0 2409.79   118.7 2363.95   131.9 2362.45   179.8  2333.4   225.6 2333.12
   244.8 2338.36   271.5 2339.07   465.1 2333.53   524.9 2336.14  559.76 2332.25
   576.1 2330.76  589.12 2332.25   601.5 2344.89     615 2350.54   618.2 2354.48
   626.5 2372.49   643.2 2391.28     660 2397.05   668.3 2406.03   680.8  2414.2
   722.5 2430.99   760.1 2453.89   772.6 2455.77   789.3 2470.49     806 2472.85
   831.1 2487.54   878.6 2509.08   893.7 2510.61   953.8  2534.9    1018 2570.67
#Mann= 5 ,-1,0
       0      .1       0     300     .06       0  402.47      .1       0
  559.76    .045       0  589.12      .1       0
#XS Ineff= 2 , 0
          524.89    2355
Permanent Ineff=
       F       F
Bank Sta=559.76,589.12
XS Rating Curve= 0 ,0
Exp/Cntr=0.3,0.1

Type RM Length L Ch R = 1 ,3293    ,285.6,281.9,277.7
XS GIS Cut Line= 4
2214467.61507909560742.7537622342214452.85034705 560873.36485331
2214302.93152947561331.0715463832214211.93136452561762.333036177
#Sta/Elev= 30
       0 2416.76   106.6 2363.47   123.2 2360.62     173 2337.67   215.4 2327.57
   282.8 2326.24   358.5 2333.72   417.5 2333.43   430.1 2327.97   496.4 2326.95
   518.5 2331.99   539.5 2331.05  550.752326.097   560.6 2324.62  590.132326.098
   602.7 2329.95   613.8 2340.46   623.4 2344.75   656.1 2379.03   667.8 2387.78
     759 2434.06   795.1 2458.65   811.5  2461.9   827.8  2475.1   889.1 2509.99
   900.7 2513.19   921.8 2531.56   934.1 2534.06   966.8 2558.53  1053.8 2609.61
#Mann= 5 ,-1,0
       0      .1       0  311.44     .06       0  411.44      .1       0
  550.75    .045       0  590.13      .1       0
#XS Ineff= 2 , 0
          514.28    2350
Permanent Ineff=
       F       F
Bank Sta=550.75,590.13
XS Rating Curve= 0 ,0
Exp/Cntr(USF)=0,0
Exp/Cntr=0.3,0.1

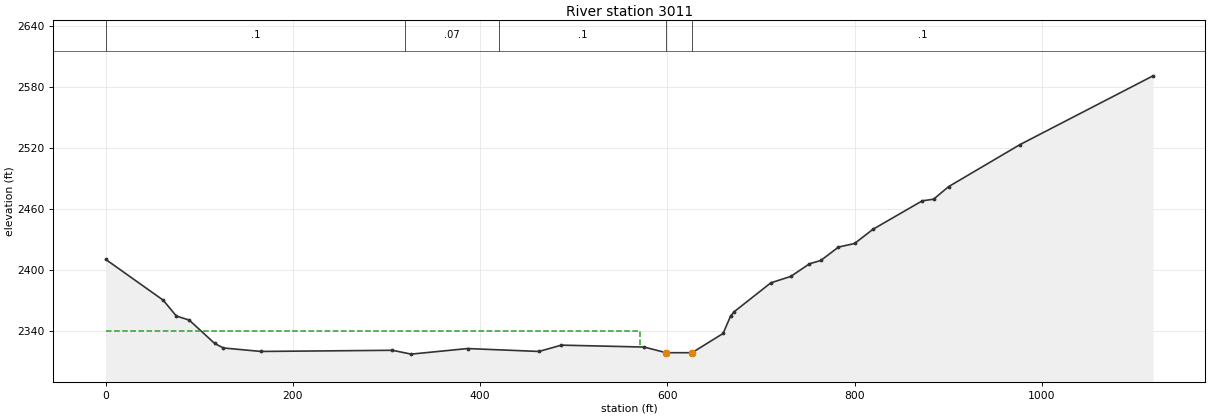
Type RM Length L Ch R = 1 ,3011    ,453.3,457.3,461.6
XS GIS Cut Line= 5
2214157.28827745560647.0170144452214080.66326385560787.139106083
 2214049.3738091561159.926704376  2214039.987357561261.163206492
2213997.27217441561742.808356661
#Sta/Elev= 30
       0  2410.2    61.4 2370.14    75.4 2354.58    89.1 2350.63   116.4 2327.61
   125.6 2323.21   165.8 2319.78   306.3 2320.92   326.3 2317.15   386.5 2322.63
   462.8 2319.78   486.9 2325.99   575.2  2324.1  598.632318.566  626.382318.536
   659.6 2337.46   667.6 2354.56   671.6 2358.92   710.6 2387.21   731.9 2393.51
   751.9 2405.92     764 2409.19   782.9 2422.35   800.1 2425.87   819.7 2439.82
   872.4  2467.8   884.5 2469.39   900.5 2481.72   976.8 2523.05    1119 2590.64
#Mann= 5 ,-1,0
       0      .1       0   319.7     .07       0   419.7      .1       0
  598.63    .045       0  626.38      .1       0
#XS Ineff= 2 , 0
          571.22    2340
Permanent Ineff=
       F       F
Bank Sta=598.63,626.38
XS Rating Curve= 0 ,0
Exp/Cntr=0.3,0.1