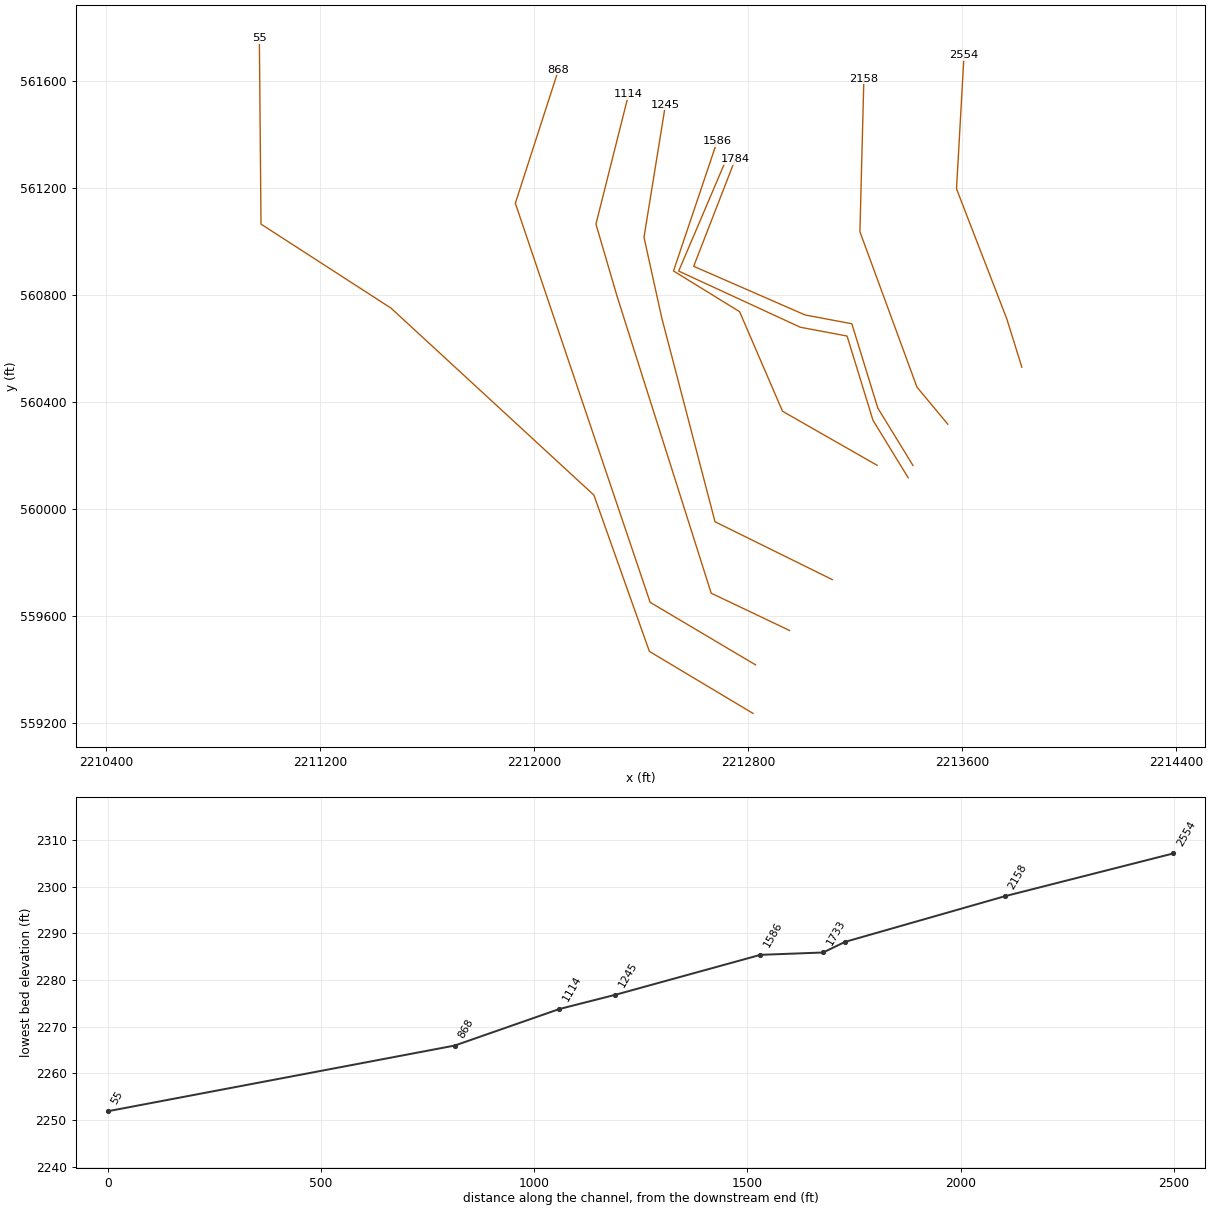
HEC-RAS study VALLEYFK.prj: VALLEYFK

--- VALLEYFK.g01 (geometry) --- (continued)

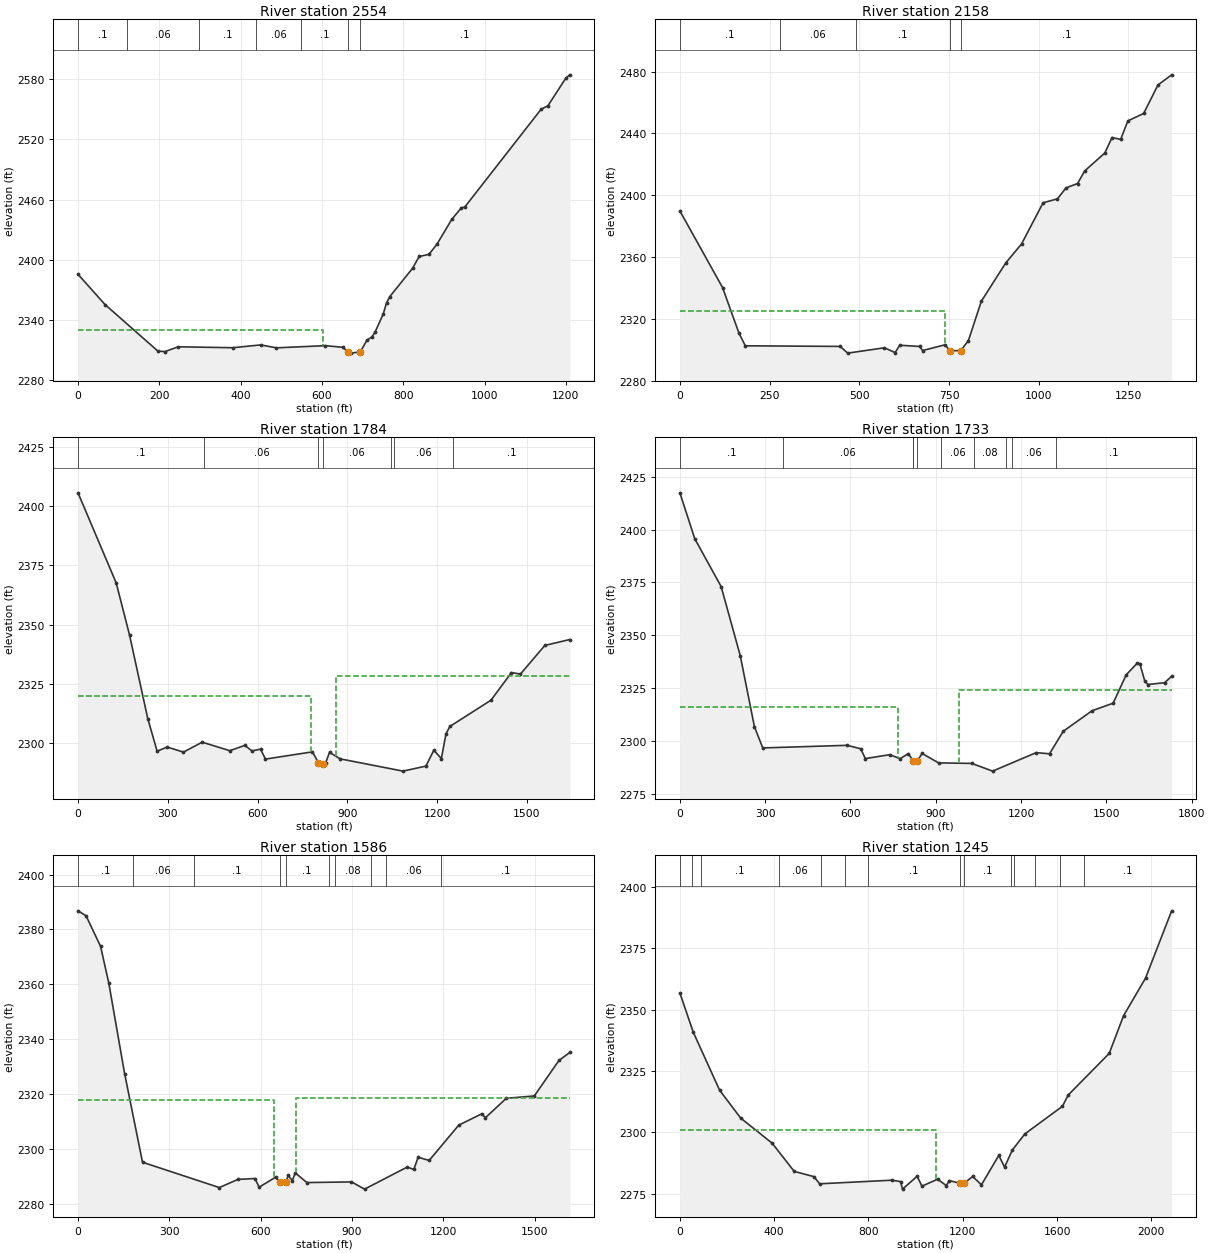
Type RM Length L Ch R = 1 ,2554    ,396.1,395.7,395.7
XS GIS Cut Line= 5
2213823.89462547560529.8026969122213767.77408875560710.031136552
2213591.79292814561165.0634751252213579.71893086561197.138043745
2213607.74337874561695.135458897
#Sta/Elev= 30
       0 2385.59    66.4  2355.5   196.4 2309.19   213.6 2308.62   246.6 2313.42
   380.8  2312.5   449.5  2315.3   488.1 2312.38   608.1 2314.55   651.7 2312.92
   663.32308.454   672.5 2307.12  694.632308.454   710.9 2320.16     723  2323.2
     731 2328.31     751 2346.19     759 2357.16     767 2363.42   823.1 2391.63
   839.2 2403.35   863.2 2405.43   883.2 2415.67   919.3 2440.22   943.3 2451.91
   951.3  2452.5  1139.2 2549.91  1155.7 2553.25  1199.7 2580.67  1209.7 2584.17
#Mann= 7 ,-1,0
       0      .1       0     120     .06       0  298.76      .1       0
  438.76     .06       0  548.76      .1       0   663.3    .045       0
  694.63      .1       0
#XS Ineff= 2 , 0
          603.86    2330
Permanent Ineff=
       F       F
Bank Sta=663.3,694.63
XS Rating Curve= 0 ,0
Exp/Cntr=0.3,0.1

Type RM Length L Ch R = 1 ,2158    ,362.9,374.6,381.9
XS GIS Cut Line= 4
2213547.12983966560316.7176091132213431.84122822560455.375533676
2213218.66791182561036.0210165322213233.44833384561607.284206976
#Sta/Elev= 30
       0 2389.86   118.9 2340.34   164.3 2311.08   182.2 2302.68   446.5 2302.28
   467.7 2297.94     570 2301.39   599.8 2298.29   612.6 2303.05   667.7 2302.26
   676.5 2299.61   739.4 2303.37   751.8 2299.46     783 2299.62     804 2306.09
     840 2331.51   908.1 2356.24   952.1 2368.54  1012.1 2395.13  1052.1  2397.7
  1076.1 2404.75  1108.1 2407.58  1128.1 2415.76  1184.2 2427.34  1204.2 2437.32
  1228.2 2436.09  1248.2 2448.06  1292.2 2452.85  1332.2  2471.3  1370.3 2477.85
#Mann= 5 ,-1,0
       0      .1       0  280.33     .06       0  490.33      .1       0
   751.8    .045       0     783      .1       0
#XS Ineff= 2 , 0
          739.38    2325
Permanent Ineff=
       F       F
Bank Sta=751.8,783
XS Rating Curve= 0 ,0
Exp/Cntr(USF)=0,0
Exp/Cntr=0.3,0.1

Type RM Length L Ch R = 1 ,1784    ,51.3,51.3,51.4
XS GIS Cut Line= 6
2213417.00641972560162.403131955 2213285.4458421560377.054600702
2213188.50646912560692.1075628952213013.66938571  560724.9977073
2212597.36116078560906.8426997882212752.60239862561306.824900527
#Sta/Elev= 30
       0 2405.55   127.7 2367.52   172.2 2345.56   233.1 2310.34   264.4 2296.57
   297.9 2298.32   352.3 2296.18   415.1 2300.37   507.2 2296.78   557.4 2299.02
   581.4 2296.69   609.9 2297.44   626.5 2293.24   783.5 2296.29   803.52291.693
     8182291.147   827.5 2291.65   840.7 2296.09     876 2293.34  1086.2 2288.16
  1162.5 2290.28  1189.2 2296.97  1214.3 2293.44  1229.7 2303.86  1242.6    2307
  1379.9 2318.07  1448.6 2329.73  1478.6 2329.11  1560.1 2341.18  1643.4 2343.67
#Mann= 7 ,-1,0
       0      .1       0  421.76     .06       0   803.5    .045       0
     818     .06       0 1045.04      .1       0 1055.04     .06       0
 1254.35      .1       0
#XS Ineff= 2 , 0
           779.6 2319.89   862.3         2328.39
Permanent Ineff=
       F       F
Bank Sta=803.5,818
XS Rating Curve= 0 ,0
Exp/Cntr(USF)=0,0
Exp/Cntr=0.3,0.1

Type RM Length L Ch R = 1 ,1733    ,155.1,146.9,142.7
XS GIS Cut Line= 6
2213399.12280063560116.5399124062213267.56222301560331.191381153
2213170.62285003560646.2443433462212995.78576662560679.134487751
 2212541.2594114560889.0061091182212724.82616132561320.031912688
#Sta/Elev= 30
       0 2417.34    52.4 2395.65   145.1 2373.07   212.3 2340.46   262.2 2306.88
   291.5 2296.85   587.9 2298.08   636.1 2296.45   652.2 2291.81   738.5 2293.67
   774.5 2291.76   803.5 2294.16   820.9 2290.73   835.72290.757   851.8 2294.25
   909.7 2289.79  1026.9 2289.53    1100 2285.89  1253.3 2294.63  1300.1 2294.07
  1348.3 2304.72  1449.5 2314.39  1523.8 2317.98    1570 2331.42  1609.1 2336.96
  1617.8 2336.64  1635.2 2328.38  1646.3  2326.8  1704.8 2327.66  1729.6 2330.66
#Mann= 10 ,-1,0
       0      .1       0  361.76     .06       0  819.92      .1       0
   820.9    .045       0   835.7      .1       0  919.92     .06       0
 1035.04     .08       0 1147.96      .1       0 1167.96     .06       0
 1321.14      .1       0
#XS Ineff= 2 , 0
          767.21  2316.2  980.33         2324.33
Permanent Ineff=
       F       F
Bank Sta=820.9,835.7
XS Rating Curve= 0 ,0
Exp/Cntr(USF)=0,0
Exp/Cntr=0.3,0.1

Type RM Length L Ch R = 1 ,1586    ,341.5,340.3,338.4
XS GIS Cut Line= 5
2213283.01794711560163.0889956982212929.44952034560365.052829722
2212768.86590775560737.3760250242212521.94062636560889.437356505
2212685.36191103561374.738473641
#Sta/Elev= 30
       0 2386.78    26.3 2385.01      74 2373.87     101 2360.51   153.1 2327.46
   211.8 2295.19     464 2285.96   524.9 2288.92   581.2 2289.26   594.6  2286.1
   648.7 2289.72  662.462287.854     6822287.871   690.5 2290.39   703.5 2288.46
   713.4 2291.32   751.5 2287.78     898 2288.02   940.9 2285.39  1081.2 2293.44
  1102.7 2292.55  1116.8 2297.01    1153 2295.84  1250.1 2308.69  1325.2 2312.81
  1337.9 2311.42  1406.3 2318.48  1498.2 2319.33  1579.3 2332.28  1614.7 2335.17
#Mann= 10 ,-1,0
       0      .1       0     180     .06       0     380      .1       0
  662.46    .045       0     682      .1       0  822.66     .06       0
  842.66     .08       0  962.66      .1       0 1012.66     .06       0
 1192.65      .1       0
#XS Ineff= 2 , 0
          643.05 2317.77  715.29         2318.65
Permanent Ineff=
       F       F
Bank Sta=662.46,682
XS Rating Curve= 0 ,0
Exp/Cntr(USF)=0,0
Exp/Cntr=0.3,0.1

Type RM Length L Ch R = 1 ,1245    ,130.7,131.4,132.8
XS GIS Cut Line= 5
2213115.23236426559735.9142007972212677.06927128559952.114041156
2212478.06817331 560713.968358172212411.64458871561015.382194608
2212491.82290414561510.596480658
#Sta/Elev= 30
       0 2356.81    56.9 2340.79   168.4  2317.2   257.7 2305.83   391.5 2295.56
   485.1 2284.06   568.2 2281.94   593.1    2279     899 2280.47     936 2279.91
   944.5 2276.83  1006.5 2282.08  1027.1 2278.04  1093.4 2280.88  1130.5 2278.26
  1142.9 2280.33 1187.852279.233 1206.782279.293  1242.1 2281.99  1279.3 2278.59
    1353 2290.57  1377.6 2285.81  1410.4 2292.77  1463.6 2299.35    1623 2310.61
  1647.3 2315.19  1821.5 2332.18  1882.3 2347.53  1975.5 2362.87  2086.3 2390.31
#Mann= 14 ,-1,0
       0      .1       0      50     .06       0      90      .1       0
     420     .06       0   598.6      .1       0   698.6     .05       0
   798.6      .1       0 1187.85    .045       0 1206.78      .1       0
 1406.01     .06       0 1416.01      .1       0 1506.01     .06       0
 1614.66     .08       0 1714.66      .1       0
#XS Ineff= 2 , 0
         1088.34    2301
Permanent Ineff=
       F       F
Bank Sta=1187.85,1206.78
XS Rating Curve= 0 ,0
Exp/Cntr(USF)=0,0
Exp/Cntr=0.3,0.1

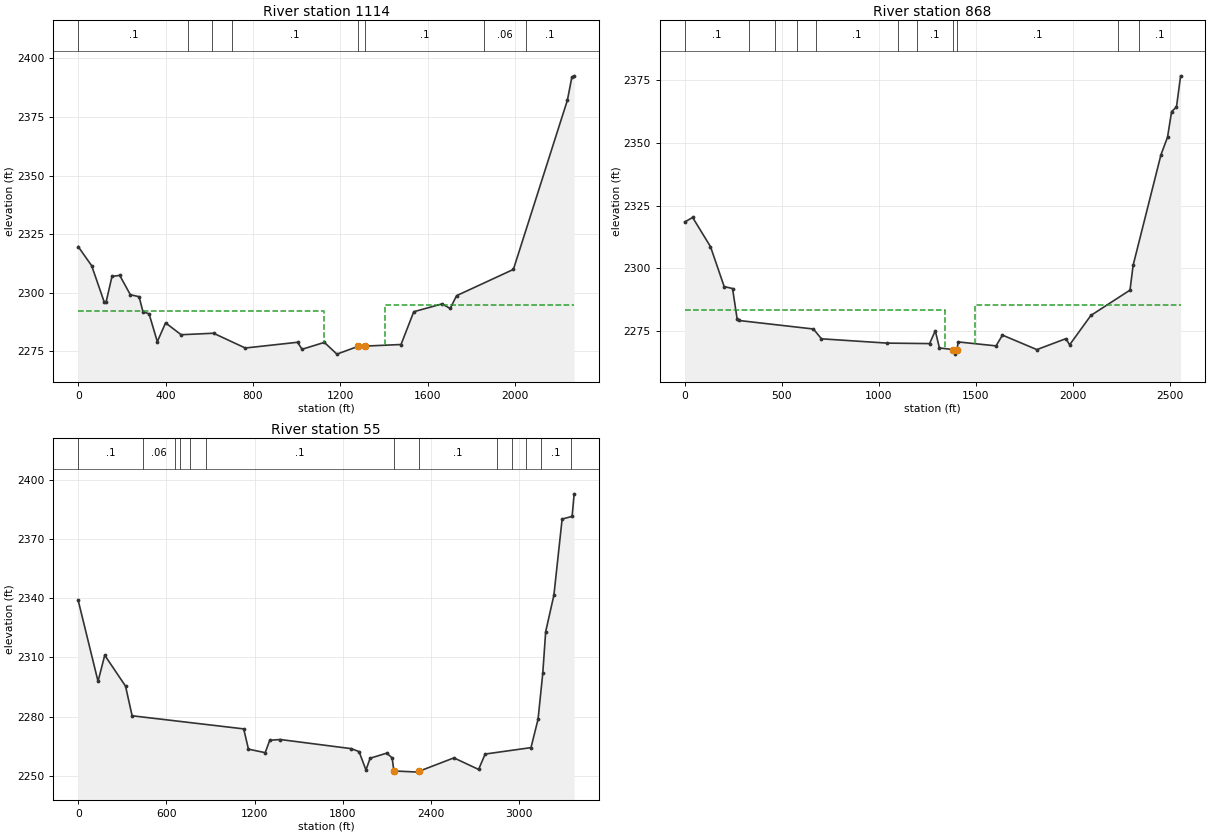
Type RM Length L Ch R = 1 ,1114    ,245.3,245.5,245.8
XS GIS Cut Line= 5
2212955.79708761559545.6476889082212662.84174072559685.037732994
2212310.82281583560795.4329994372212232.07329701561064.655608642
2212354.41263114561551.107962155
#Sta/Elev= 30
       0 2319.68    61.6 2311.52   119.2 2295.99     128 2296.14   154.6 2306.93
   190.1 2307.41   238.8 2299.14   278.7  2298.3   296.5 2291.91   324.6 2290.97
   362.3 2279.09   400.1 2287.13   471.4 2282.06   619.8  2282.7   765.2 2276.39
  1004.4 2278.84  1025.3 2275.86  1127.4 2278.79  1184.8 2273.78 1283.472277.152
  1311.72277.197  1478.5 2277.89  1536.9 2291.88  1666.1 2295.22  1703.7 2293.27
  1732.8 2298.73  1993.1 2309.94  2240.5  2382.2  2260.8    2392  2271.4 2392.59
#Mann= 8 ,-1,0
       0      .1       0  504.43     .08       0  614.43     .06       0
  704.43      .1       0 1283.47    .045       0  1311.7      .1       0
 1859.79     .06       0 2049.79      .1       0
#XS Ineff= 2 , 0
         1124.77 2292.14  1407.1         2294.72
Permanent Ineff=
       F       F
Bank Sta=1283.47,1311.7
XS Rating Curve= 0 ,0
Exp/Cntr(USF)=0,0
Exp/Cntr=0.3,0.1

Type RM Length L Ch R = 1 ,868     ,806.8,813.6,1018.8
XS GIS Cut Line= 4
2212828.43370739559417.3194986632212434.67071035559650.907717251
 2211930.7875531561142.5353416662212092.09093186561641.410239738
#Sta/Elev= 30
       0 2318.47      41 2320.28     133 2308.69   203.6  2292.8   246.8 2292.03
   270.1  2280.1   279.4 2279.32   663.6 2275.94   705.1 2272.04  1042.9 2270.33
  1262.4 2270.14    1292 2275.24  1313.1 2268.41  1385.32267.754  1393.3 2265.95
  1403.22267.725  1410.2  2270.8  1605.1 2269.23  1638.2 2273.51  1815.5 2267.75
  1965.4  2272.1  1984.4 2269.65  2093.9 2281.32  2295.7  2291.4  2311.8 2301.29
  2455.4 2345.24  2489.1 2352.18  2510.1 2362.36  2535.3 2364.22  2556.6 2376.58
#Mann= 11 ,-1,0
       0      .1       0     330     .06       0  467.83     .08       0
  577.83     .07       0  677.83      .1       0 1097.83     .06       0
 1197.83      .1       0  1385.3    .045       0  1403.2      .1       0
 2232.27     .07       0 2342.27      .1       0
#XS Ineff= 2 , 0
         1344.26 2283.43 1497.27         2285.65
Permanent Ineff=
       F       F
Bank Sta=1385.3,1403.2
XS Rating Curve= 0 ,0
Exp/Cntr(USF)=0,0
Exp/Cntr=0.3,0.1

Type RM Length L Ch R = 1 ,55      ,,,
XS GIS Cut Line= 6
2212819.05296506559235.8981057342212431.79675495559467.527988413
2212224.42020092560051.6985073212211466.22575026560750.464573383
2210980.19888236 561064.566164092210974.03452536561758.908341872
#Sta/Elev= 30
       0 2338.85     135 2297.86   180.5 2311.11     322 2295.46   366.9 2280.43
  1126.4 2273.79  1158.5 2263.52  1272.7 2261.74  1303.5 2268.01  1374.3 2268.41
  1858.3 2263.78  1911.4 2262.28  1958.4 2252.97  1986.7 2258.91  2099.9 2261.51
  2136.7 2259.09  2148.22252.476    2319 2251.88 2320.242252.333    2557  2259.1
  2725.1 2253.24  2769.5 2261.04  3081.5  2264.3  3129.6 2278.65  3161.8 2302.02
  3181.5 2323.05  3237.5 2341.55  3293.5 2380.12  3361.5 2381.46  3375.3 2392.89
#Mann= 13 ,-1,0
       0      .1       0     440     .06       0  661.24     .08       0
  691.24      .1       0  761.24     .08       0  871.24      .1       0
  2148.2    .045       0 2320.24      .1       0  2850.9     .05       0
  2950.9     .08       0  3050.9     .07       0  3150.9      .1       0
  3350.9     .06       0
Bank Sta=2148.2,2320.24
XS Rating Curve= 0 ,0
Exp/Cntr(USF)=0,0
Exp/Cntr=0.3,0.1
LCMann Table=0

Chan Stop Cuts=-1
Use User Specified Reach Order=0
Composite Channel Slope=5